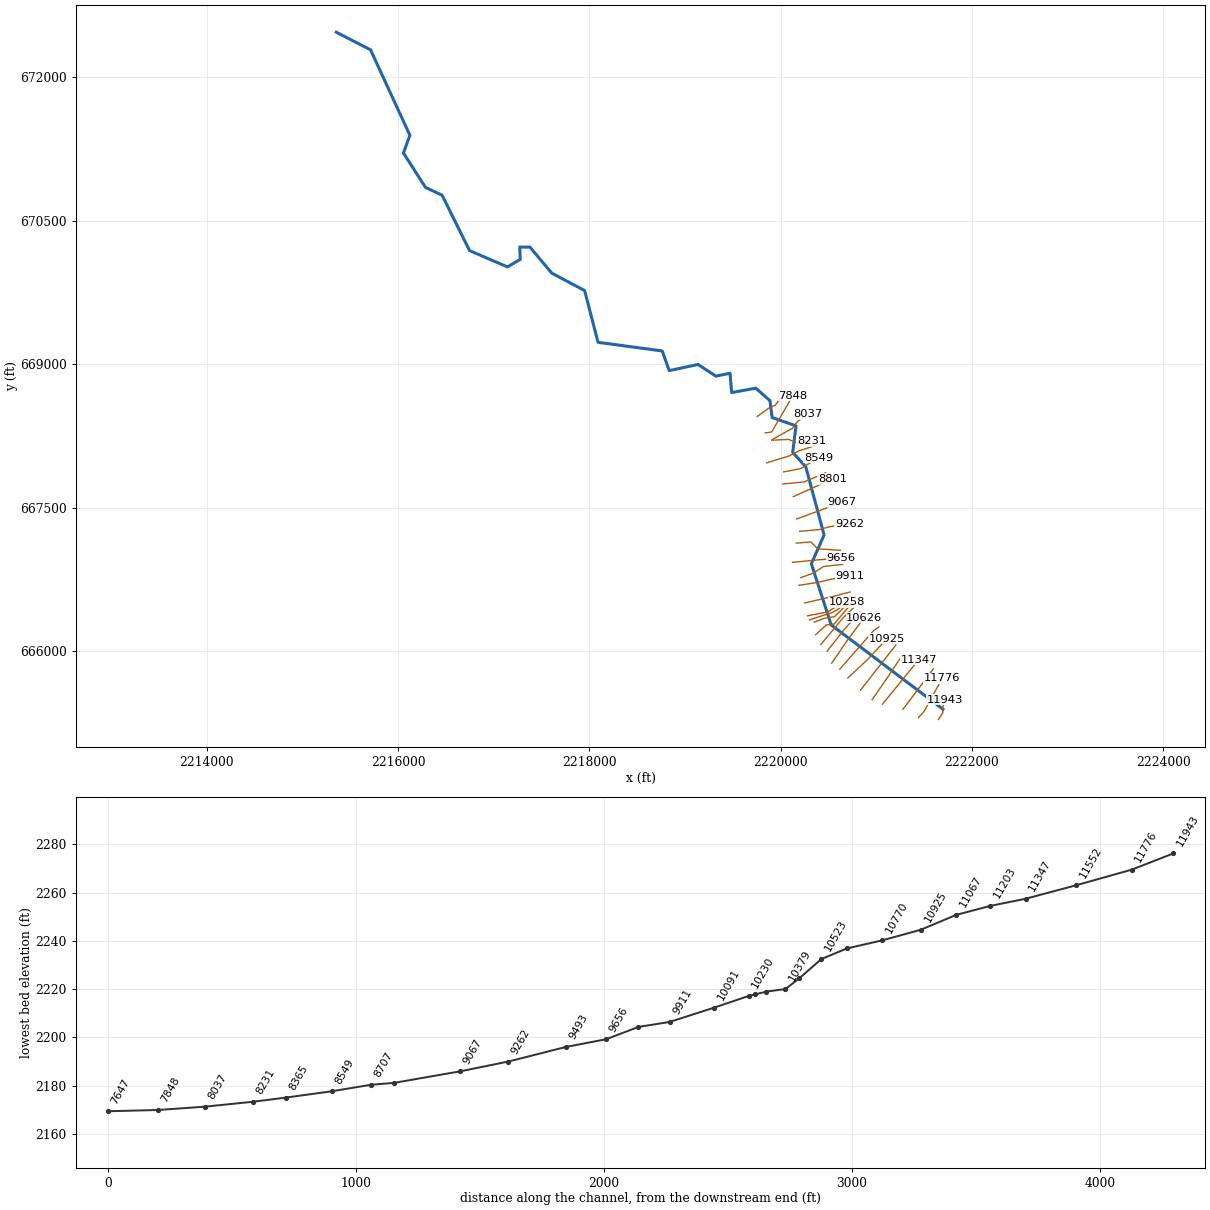
--- JACKSONFK.prj (project) ---

Proj Title=JACKSONFK
Current Plan=p01
Default Exp/Contr=0,0
English Units
Geom File=g01
Flow File=f01
Plan File=p01
BEGIN DESCRIPTION:
---------- MODELED AS PART OF WVEMD CTP PROGRAM, 2023----------
Stream Name: Jackson Fork
Flood Zone:  AFH
Upshur County, WV
HEC-RAS Version: RAS 6.3
Vertical Datum: NAVD88
Projection: NAD 1983 StatePlane West Virginia S FIPS 4702 (US Feet)
Terrain: 1-meter LIDAR (FEMA Region III 3DEP collected 2016-2018)
Land Use: 2019 NLCD
Hydrologic Method:
WV SIR2010-5033 regression equations
Additional Model Notes:
None
END DESCRIPTION:
DSS Export Rating Curves= 0
DSS Export Rating Curve Sorted= 0
DSS Export Volume Flow Curves= 0
DXF OffsetX= 0
DXF OffsetY= 0
DXF ScaleX= 0
DXF ScaleY= 0

--- JACKSONFK.p01 (plan) ---

Plan Title=Floodplain
Program Version=4.00
Geom File=g01
Flow File=f01
K Sum by GR=0
Std Step Tol=0.01
Critical Tol=0.01
Num of Std Step Trials=20
Max Error Tol=0.3
Flow Tol Ratio=0.001
Split Flow NTrial=30
Split Flow Tol=0.02
Split Flow Ratio=0.02
Log Output Level=0
Friction Slope Method=1
Unsteady Friction Slope Method=2
Unsteady Bridges Friction Slope Method=1
Global Log Level=0
CheckData=False
Run HTab=0
Run UNet=0
Run PostProcess=0
UNET Theta=0
UNET Theta Warmup=0
UNET ZTol=0
UNET ZSATol=0
UNET MxIter=0
UNET MaxInSteps=0
UNET DtIC=0
UNET DtMin=0
UNET MaxCRTS=0
UNET WFStab=0
UNET SFStab=0
UNET WFX=0
UNET SFX=0
UNET DSS MLevel=0
UNET DZMax Abort=0
UNET Convert EG Bridges=0
UNET Use Existing IB Tables=0
UNET Froude Limit=0
UNET Froude Power=0
Write IC File=0
Echo Input=False
Echo Output=False
Write Detailed=0

--- JACKSONFK.f01 (steady flow) ---

Flow Title=Flows
Program Version=6.30
Number of Profiles= 1
Profile Names=01pct
River Rch & RM=JACKSONFK,Main            ,11943
     328
River Rch & RM=JACKSONFK,Main            ,9493
     395
River Rch & RM=JACKSONFK,Main            ,8037
     448
River Rch & RM=JACKSONFK,Main            ,4479
     671
Boundary for River Rch & Prof#=JACKSONFK,Main            , 1
Up Type= 0
Dn Type= 3
Dn Slope=0.01487
DSS Import GetInterval= 0
DSS Import GetPeak= 0
DSS Import FillOption= 0

--- JACKSONFK.g01 (geometry) ---

Geom Title=Geometry
Program Version=6.30

River Reach=JACKSONFK       ,Main
Reach XY= 30
     2221696.767      665392.766     2220528.017      666274.294
     2220320.949      666913.298     2220454.043      667214.743
     2220262.171      667927.806     2220125.699      668077.727
     2220161.155      668355.077     2219910.962      668441.842
     2219887.553      668619.035     2219739.721      668748.953
     2219488.154      668703.053      2219470.47      668905.084
     2219321.893      668874.837     2219136.774      668996.857
     2218834.556      668932.728     2218762.328      669138.079
     2218090.931      669228.478     2217950.939      669769.128
     2217608.344      669951.013     2217378.783      670223.871
     2217272.674      670224.271      2217277.51      670094.353
      2217143.07      670016.574     2216747.792      670187.413
     2216460.941       670766.18     2216287.555      670847.508
     2216056.821      671207.473     2216124.355      671392.335
     2215713.195      672285.653     2215354.231      672470.257

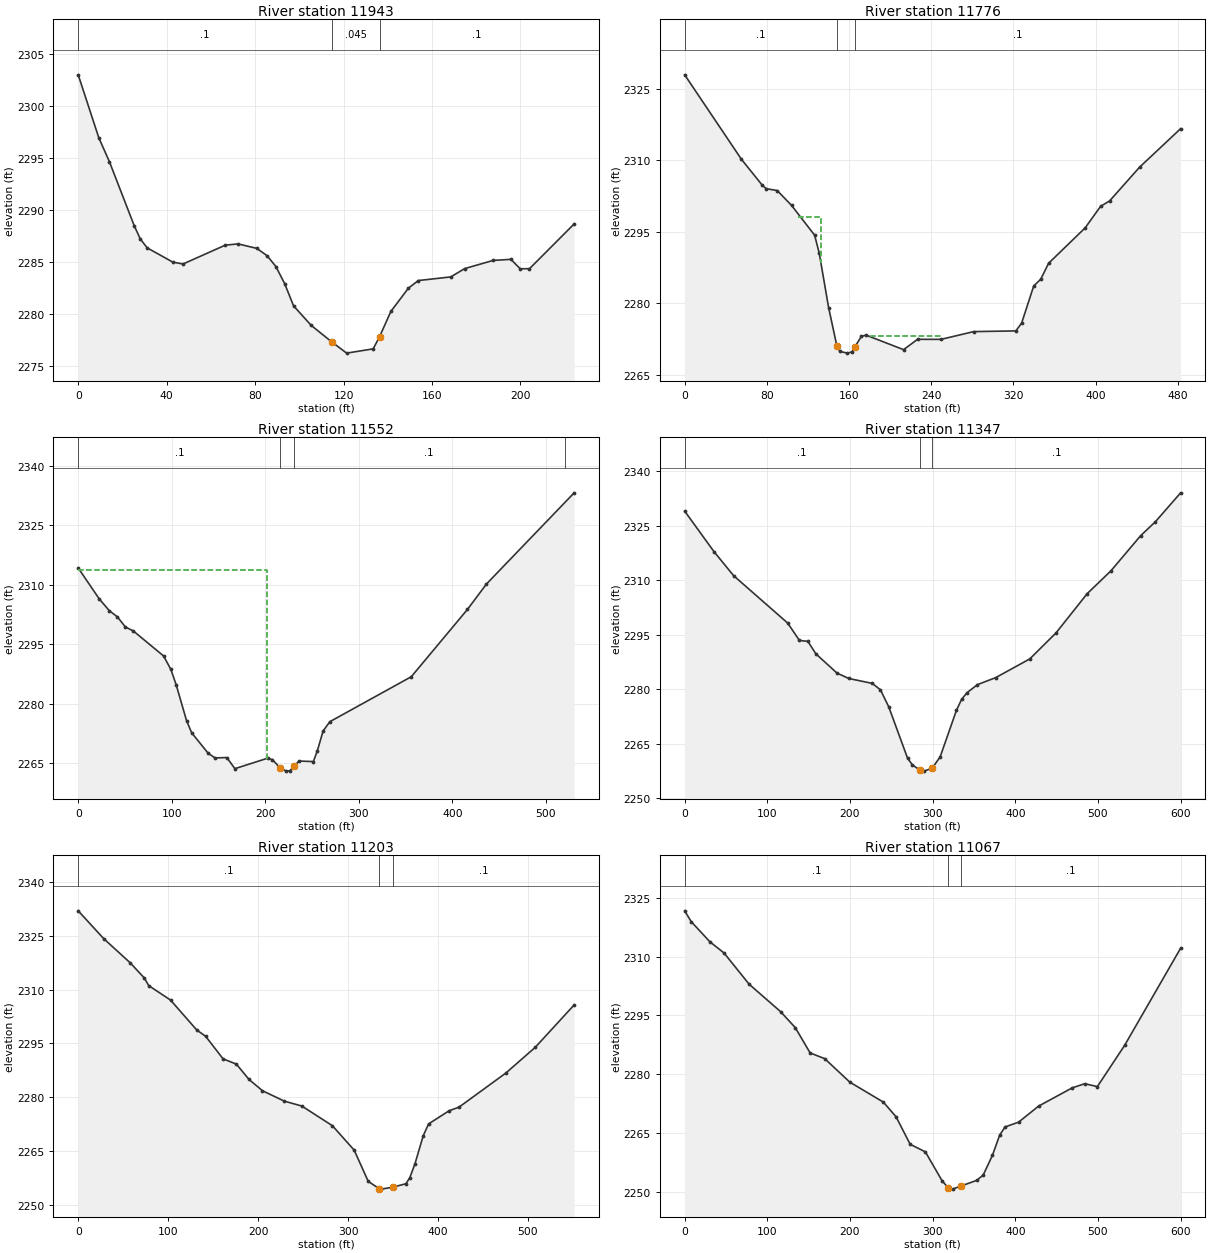
Type RM Length L Ch R = 1 ,11943   ,170.7,167.9,161.3
XS GIS Cut Line= 4
2221648.93306094665285.328738749 2221694.8043714665356.365559799
2221695.12292216665416.8902055362221719.01422969665492.386737323
#Sta/Elev= 30
       0 2302.96     9.3 2296.92    14.1 2294.62    25.4 2288.43    28.1 2287.19
    31.2 2286.34    42.7 2284.98    47.4 2284.79    66.5  2286.6    72.3 2286.72
    80.8 2286.29    85.4 2285.59    89.4 2284.55    93.4 2282.89    97.4 2280.77
   105.4 2278.89   114.6 2277.32   121.4 2276.23   133.4 2276.64   136.3 2277.81
   141.4 2280.23   149.3 2282.46   153.8  2283.2   168.5 2283.55   174.8 2284.35
   187.6 2285.13   195.7 2285.24   199.9 2284.33   204.1 2284.34   224.3 2288.64
#Mann= 3 ,-1,0
       0      .1       0   114.6    .045       0   136.3      .1       0
Bank Sta=114.6,136.3
XS Rating Curve= 0 ,0
Exp/Cntr(USF)=0,0
Exp/Cntr=0.3,0.1

Type RM Length L Ch R = 1 ,11776   ,223.5,223.6,219.7
XS GIS Cut Line= 4
2221441.15863969665306.1253576912221501.23936646665373.234551041
2221646.89586717665639.9717642622221689.72516172665717.781210041
#Sta/Elev= 30
       0 2327.98    55.3 2310.22    75.1 2304.91    79.3 2304.07    90.1 2303.67
     104 2300.56   126.5  2294.3     131 2290.51   140.1  2279.1   148.2 2270.98
   151.2 2269.87   158.4 2269.52   162.9 2269.78   165.9  2270.9     172 2273.04
   176.6  2273.3   213.1 2270.25   226.7 2272.42   249.5 2272.41   281.4 2274.04
   322.4 2274.19     328 2275.82   339.8 2283.63   346.6 2285.04   354.3  2288.4
   389.9 2295.84   404.9 2300.36   413.6 2301.48   442.9 2308.59   482.8 2316.67
#Mann= 3 ,0,0
       0      .1       0   148.2    .045       0   165.9      .1       0
#XS Ineff= 2 ,-1
110.7955132.6707 2298.19181.1446248.1629 2273.05
Permanent Ineff=
       T       T
Bank Sta=148.2,165.9
XS Rating Curve= 0 ,0
Exp/Cntr(USF)=0,0
Exp/Cntr=0.3,0.1

Type RM Length L Ch R = 1 ,11552   ,204.5,205,203.4
XS GIS Cut Line= 2
2221278.62676287665392.1780810492221596.98491038665816.120692243
#Sta/Elev= 30
       0 2314.26    22.6 2306.42    33.2 2303.51    41.8 2301.95    50.4  2299.4
      59 2298.37    91.3 2292.07      99 2288.71   104.7 2284.84   115.8 2275.79
   121.3 2272.71     139 2267.54   146.3 2266.38   158.9 2266.47   167.5 2263.67
   202.4  2266.3   207.5 2265.95   216.1 2263.82   222.4 2263.05   226.4 2263.15
   230.4 2264.24   236.1 2265.59   251.4 2265.46   255.7 2268.22   261.8 2273.15
     269 2275.51   356.1 2286.85   416.1  2303.8   436.4  2310.2   530.2  2333.2
#Mann= 4 ,-1,0
       0      .1       0   216.1    .045       0   230.4      .1       0
     520     .06       0
#XS Ineff= 2 , 0
        201.3228 2313.77
Permanent Ineff=
       T       F
Bank Sta=216.1,230.4
XS Rating Curve= 0 ,0
Exp/Cntr(USF)=0,0
Exp/Cntr=0.3,0.1

Type RM Length L Ch R = 1 ,11347   ,142.2,143.5,144.6
XS GIS Cut Line= 2
2221064.45257637665445.5606301962221443.46080146665910.697991966
#Sta/Elev= 30
       0 2328.98    35.6 2317.79    59.2 2311.22   124.6 2298.18   138.8 2293.41
   149.1 2293.13   158.7 2289.72   184.3 2284.41   198.5 2282.93     227 2281.58
   236.9 2279.79   246.9 2275.12   269.6 2261.03   275.3 2259.22   284.22257.757
   289.5 2257.44   299.42258.226   309.1 2261.38   328.8 2274.18     335 2277.17
   341.5    2279   354.2 2281.24   376.2 2283.16   417.5 2288.31   449.2 2295.46
   487.1  2306.3   515.5  2312.5   551.6 2322.21   569.5 2326.06     600 2334.01
#Mann= 3 ,-1,0
       0      .1       0   284.2    .045       0   299.4      .1       0
Bank Sta=284.2,299.4
XS Rating Curve= 0 ,0
Exp/Cntr(USF)=0,0
Exp/Cntr=0.3,0.1

Type RM Length L Ch R = 1 ,11203   ,137.6,136.6,135.6
XS GIS Cut Line= 3
2220956.06644353 665492.709077152221123.16194925665734.069252077
2221265.50256523 665949.12735666
#Sta/Elev= 30
       0 2331.93    28.3  2324.2    57.9 2317.44    73.5 2313.23    78.4 2311.11
   102.7 2307.08   131.9 2298.73   141.7    2297   161.1 2290.72   175.9 2289.25
   189.9    2285   204.9 2281.84   229.2 2278.95   248.7 2277.58   282.7  2272.1
   306.9  2265.3   322.5 2256.62   334.9 2254.53   336.9 2254.45   349.82254.992
   364.4 2255.95   368.7 2257.61   374.5 2261.52   383.6 2269.26   389.6  2272.6
   412.4 2276.26   423.5 2277.28   475.5 2286.76   508.3 2293.94   551.5 2305.74
#Mann= 3 ,-1,0
       0      .1       0   334.9    .045       0   349.8      .1       0
Bank Sta=334.9,349.8
XS Rating Curve= 0 ,0
Exp/Cntr(USF)=0,0
Exp/Cntr=0.3,0.1

Type RM Length L Ch R = 1 ,11067   ,142.3,142,140.2
XS GIS Cut Line= 2
2220834.72541757665591.6685467512221203.98123418666064.585179892
#Sta/Elev= 30
       0 2321.68     7.8 2318.95    30.6 2313.77    47.6 2310.94      78 2302.97
   116.1 2295.97   133.9 2291.88   151.8 2285.45   169.4    2284   199.8 2278.01
   240.4 2272.92   255.7 2269.19   272.8 2262.17   291.2 2260.24   311.5 2252.84
   318.92251.084   324.1 2250.74   333.92251.504   353.3 2252.97   361.2 2254.35
   372.4 2259.39   381.1 2264.51   387.6 2266.59   403.9  2267.8   428.2  2271.9
   468.8 2276.55     484 2277.61   499.3 2276.88   532.2 2287.37     600 2312.15
#Mann= 3 ,-1,0
       0      .1       0   318.9    .045       0   333.9      .1       0
Bank Sta=318.9,333.9
XS Rating Curve= 0 ,0
Exp/Cntr(USF)=0,0
Exp/Cntr=0.3,0.1

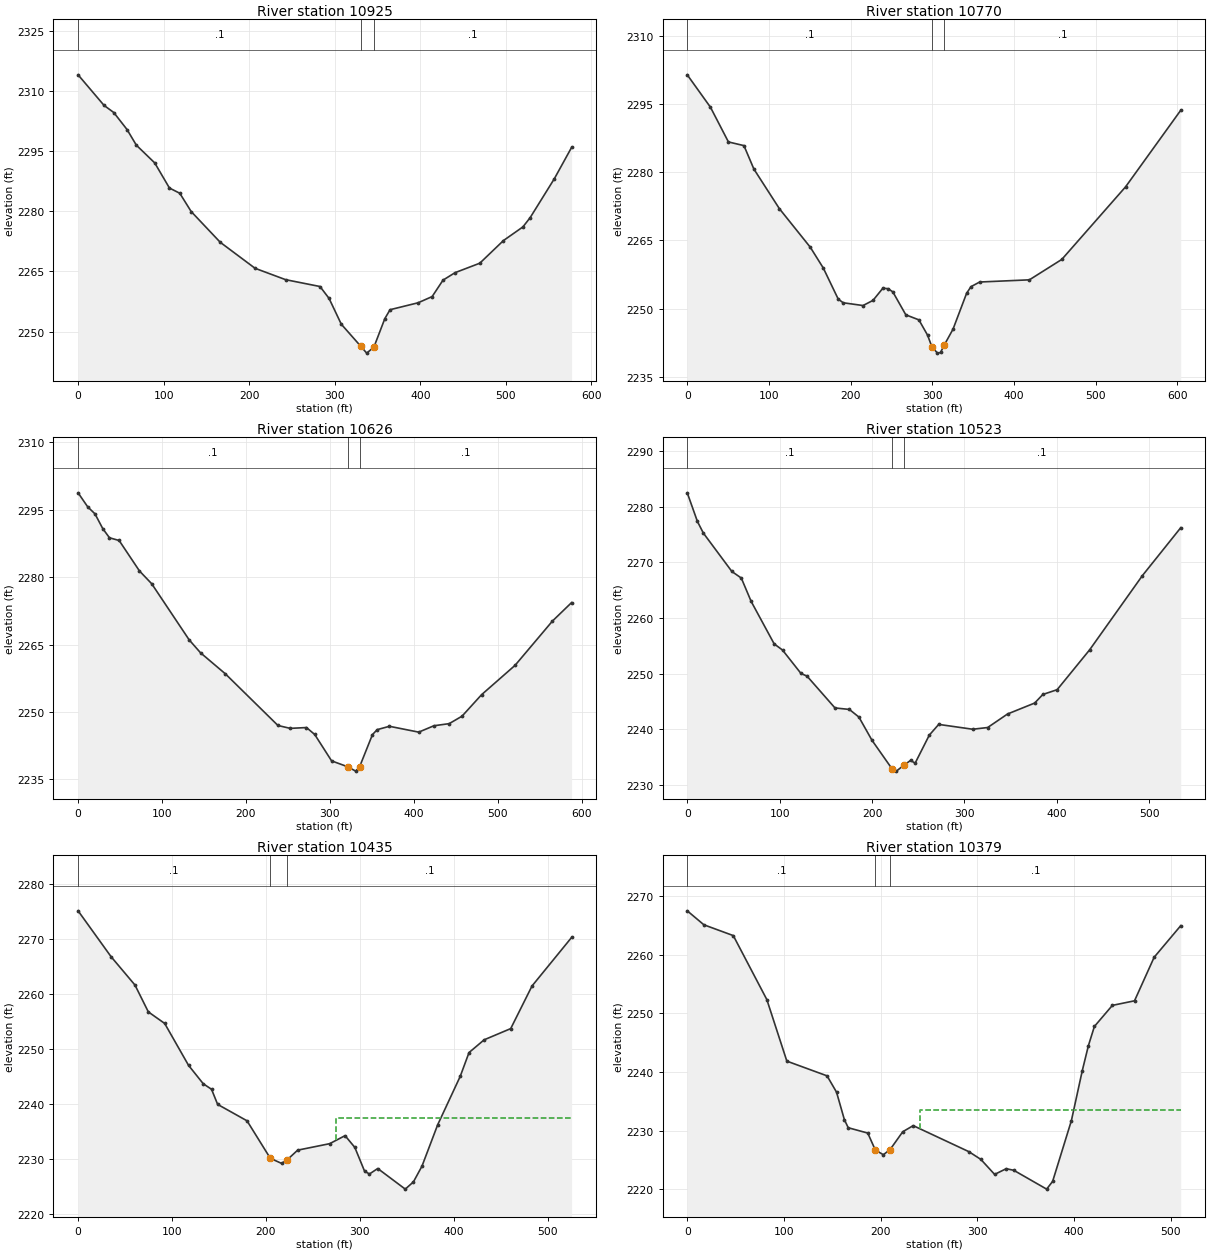
Type RM Length L Ch R = 1 ,10925   ,154.6,155.1,155.4
XS GIS Cut Line= 3
2220702.32882373665720.1446266012220905.00948345665908.900660838
2221109.23732377666128.600307246
#Sta/Elev= 30
       0 2314.09    30.3 2306.47    41.7 2304.68    57.2 2300.44    68.1 2296.53
    89.6  2292.1   106.8 2285.83   118.9 2284.52   132.2 2279.96   166.2 2272.28
   206.9 2265.79   242.6 2262.95   282.8 2261.24   293.4 2258.27   307.7 2251.83
   330.6 2246.29   337.4 2244.61   345.8  2246.1   358.6 2253.23   364.7 2255.45
   397.5 2257.18   413.9 2258.73   426.6 2262.83   440.7  2264.7   469.6 2267.06
   497.3 2272.72     520 2276.12   528.5 2278.44   556.8 2288.17   576.9 2295.96
#Mann= 3 ,-1,0
       0      .1       0   330.6    .045       0   345.8      .1       0
Bank Sta=330.6,345.8
XS Rating Curve= 0 ,0
Exp/Cntr(USF)=0,0
Exp/Cntr=0.3,0.1

Type RM Length L Ch R = 1 ,10770   ,142.1,143.2,143.9
XS GIS Cut Line= 3
2220618.44294333665811.797406676 2220970.7430219666214.354096536
2221027.59184017666253.984629478
#Sta/Elev= 30
       0  2301.4    28.4 2294.28    50.4 2286.65    69.4 2285.84    81.6 2280.68
   112.8 2271.98   150.7 2263.49   166.6 2258.92   184.8 2252.12   190.9  2251.3
   215.2 2250.69   227.4 2251.82   239.5  2254.5     246 2254.39   251.7 2253.69
   267.6 2248.65   283.6 2247.54   294.2 2244.19   299.42241.678   306.3 2240.23
   310.1 2240.37   314.4 2241.92   325.4  2245.5     342 2253.37   347.3 2254.83
     358 2255.86   418.9 2256.34   458.6 2260.83   536.7 2276.79   604.2 2293.61
#Mann= 3 ,-1,0
       0      .1       0   299.4    .045       0   314.4      .1       0
Bank Sta=299.4,314.4
XS Rating Curve= 0 ,0
Exp/Cntr(USF)=0,0
Exp/Cntr=0.3,0.1

Type RM Length L Ch R = 1 ,10626   ,102.3,103,102.5
XS GIS Cut Line= 3
2220532.38820635665872.9506249582220706.08398454666125.599029602
2220874.14028942 666351.17796232
#Sta/Elev= 30
       0 2298.75    11.5 2295.62    20.1 2294.08    29.4 2290.79    37.4 2288.75
    48.9 2288.15    73.1 2281.38    87.7 2278.53   132.3 2266.06   145.9 2263.17
   175.5 2258.49   238.1 2247.01   252.7 2246.37   272.1 2246.55   281.9 2245.01
     302 2239.14   321.12237.838   330.7 2236.86   335.32237.798   350.7 2244.99
   356.4 2246.09   370.9 2246.83   405.8 2245.53   423.9 2246.95   442.1 2247.42
   457.4 2249.08   480.7 2253.86   520.6 2260.39   565.1 2270.23   587.9 2274.34
#Mann= 3 ,-1,0
       0      .1       0   321.1    .045       0   335.3      .1       0
Bank Sta=321.1,335.3
XS Rating Curve= 0 ,0
Exp/Cntr(USF)=0,0
Exp/Cntr=0.3,0.1

Type RM Length L Ch R = 1 ,10523   ,88.9,88.6,88.4
XS GIS Cut Line= 3
2220485.39836045665999.1687739382220661.97033241666223.860535957
2220827.89813323666408.752356647
#Sta/Elev= 30
       0 2282.48      11 2277.33    17.4 2275.25    48.3 2268.34    58.5 2267.16
    69.2 2262.95    94.1 2255.32   103.1 2254.22   123.1 2250.01   129.7 2249.52
   159.9 2243.81   175.5 2243.54   185.8 2242.17     200 2237.99   221.82232.833
   226.4 2232.45   234.32233.492   241.7 2234.37   246.7 2233.89     262 2238.92
   272.2 2240.85     309 2239.98   325.2 2240.29   346.7 2242.72   376.1 2244.69
   384.9 2246.23   400.4 2247.09   435.6 2254.26   492.7  2267.6   534.2 2276.21
#Mann= 3 ,-1,0
       0      .1       0   221.8    .045       0   234.3      .1       0
Bank Sta=221.8,234.3
XS Rating Curve= 0 ,0
Exp/Cntr(USF)=0,0
Exp/Cntr=0.3,0.1

Type RM Length L Ch R = 1 ,10435   ,65.1,56.2,45.2
XS GIS Cut Line= 4
2220421.01734353 666070.949907752220552.28720074666227.918926536
2220650.70875535666346.3207967412220770.59064893666462.502631879
#Sta/Elev= 30
       0 2275.15    35.1 2266.81    60.6 2261.64    74.8 2256.76    92.2 2254.66
   117.6 2247.04   133.3 2243.68   142.1 2242.68   148.6 2239.93   179.9 2236.94
   204.72230.119   216.7 2229.19   222.5 2229.82   233.8  2231.6   267.9 2232.78
   284.3 2234.24   294.7  2232.1   305.1 2227.76   310.3 2227.27   319.1 2228.26
   348.4 2224.51   357.1 2225.83   366.2 2228.69   382.9 2236.21   406.9 2245.02
   416.3 2249.36   432.4 2251.68   460.7 2253.72   483.4 2261.48   525.5  2270.3
#Mann= 3 ,-1,0
       0      .1       0   204.7    .045       0   222.5      .1       0
#XS Ineff= 2 , 0
                          274.82         2237.41
Permanent Ineff=
       F       F
Bank Sta=204.7,222.5
XS Rating Curve= 0 ,0
Exp/Cntr(USF)=0,0
Exp/Cntr=0.3,0.1

Type RM Length L Ch R = 1 ,10379   ,76.5,77.1,77.2
XS GIS Cut Line= 4
2220364.77645518666172.3315091132220478.19185266666274.205918898
2220558.85312674666283.8260708522220737.93595542666494.729402155
#Sta/Elev= 30
       0 2267.46    17.2 2265.08    47.6 2263.24    82.3 2252.34     103 2241.85
   144.6 2239.34   154.4 2236.56   162.5 2231.88   166.5  2230.5   186.7 2229.59
   194.52226.707   202.8  2225.9   209.82226.786   222.9 2229.82   233.7 2230.86
   291.3 2226.42   303.7  2225.1   317.9 2222.55   329.9 2223.52   337.7 2223.25
   371.7 2220.04   377.9 2221.36   397.3 2231.71   408.6 2240.25   414.9 2244.49
   421.1 2247.76   439.7 2251.35   462.6 2252.13   482.9 2259.55   510.4 2264.93
#Mann= 3 ,-1,0
       0      .1       0   194.5    .045       0   209.8      .1       0
#XS Ineff= 2 , 0
                          240.68         2233.57
Permanent Ineff=
       F       F
Bank Sta=194.5,209.8
XS Rating Curve= 0 ,0
Exp/Cntr(USF)=0,0
Exp/Cntr=0.3,0.1

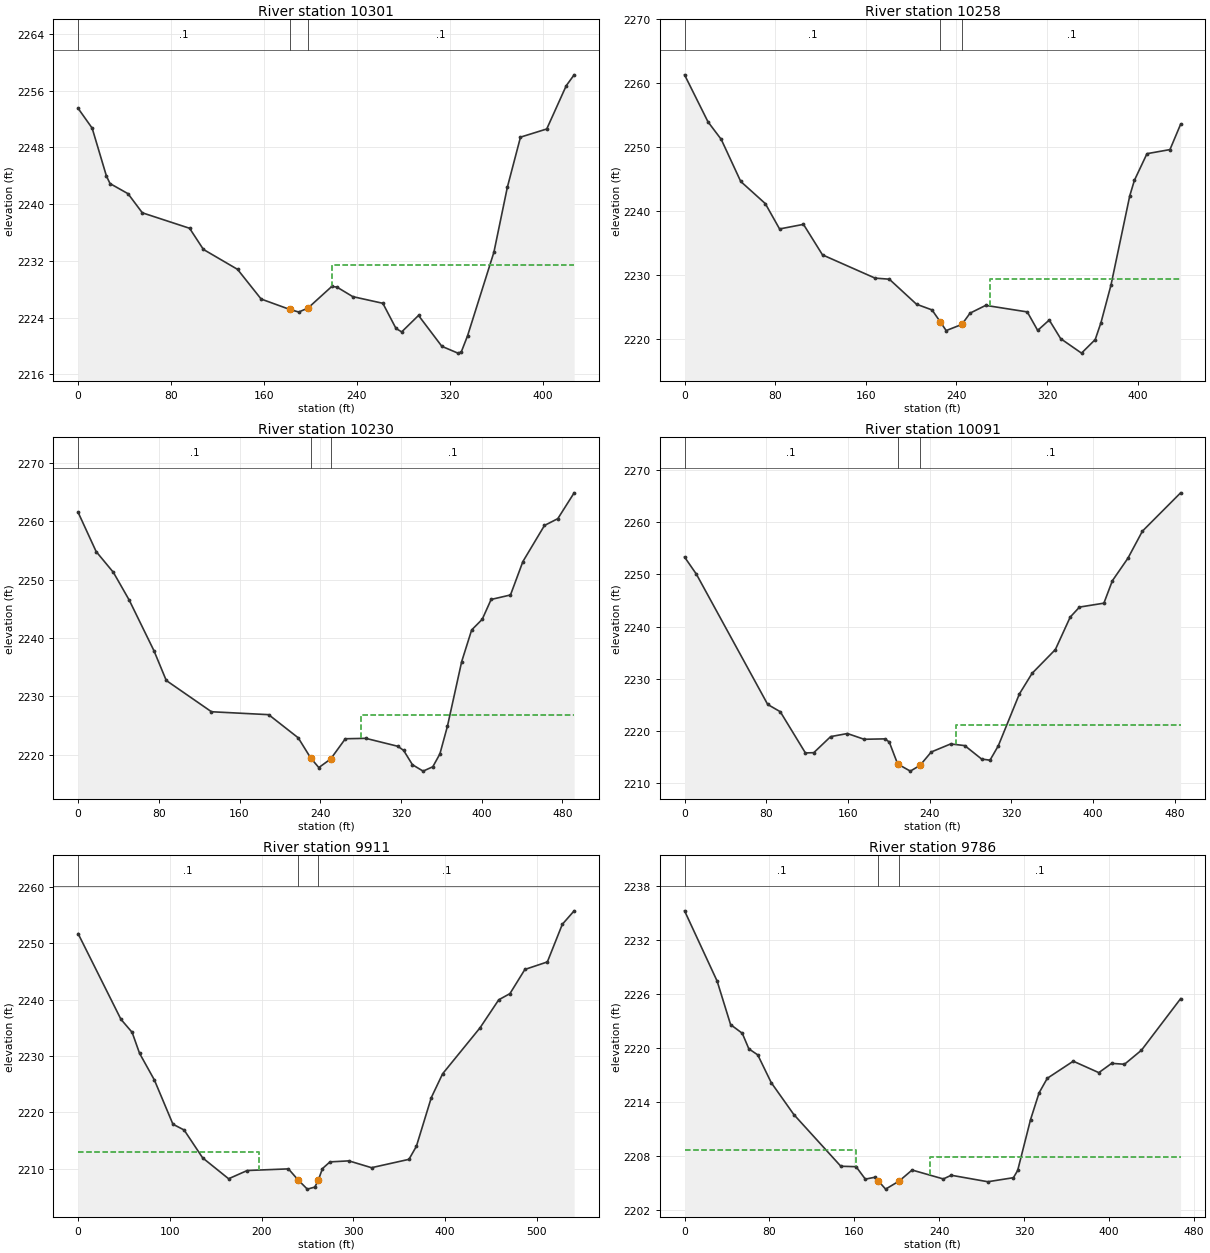
Type RM Length L Ch R = 1 ,10301   ,42,43.5,45.7
XS GIS Cut Line= 4
2220350.63779185 666303.108594792220453.67627939666343.029265353
2220563.18838918 666360.831726552220708.84488988666505.948758732
#Sta/Elev= 30
       0 2253.49    12.1  2250.7    24.4 2243.95    27.5 2242.89      43 2241.46
    55.3 2238.77      96 2236.59   107.9 2233.61   137.3  2230.8   157.6 2226.62
   182.32225.152     190 2224.79     198 2225.36   218.4 2228.39   222.8 2228.31
   236.5 2226.96   262.4 2226.02   273.7 2222.48   278.6 2221.99   293.1 2224.31
   313.2 2219.96     327    2219   329.9 2219.16   335.3 2221.43     358 2233.21
   369.6 2242.38   380.9 2249.43   403.5 2250.58   420.3 2256.68   427.1 2258.21
#Mann= 3 ,-1,0
       0      .1       0   182.3    .045       0     198      .1       0
#XS Ineff= 2 , 0
                          218.87         2231.36
Permanent Ineff=
       F       F
Bank Sta=182.3,198
XS Rating Curve= 0 ,0
Exp/Cntr(USF)=0,0
Exp/Cntr=0.3,0.1

Type RM Length L Ch R = 1 ,10258   ,24.4,28,31.8
XS GIS Cut Line= 5
2220300.52619501666326.0975851642220493.86733063666390.136707808
2220536.34076624666401.9348843652220591.79219606666433.003415965
2220691.56689904666511.118997293
#Sta/Elev= 30
       0 2261.31    20.7 2253.96    32.4 2251.22    49.6 2244.65    71.3 2241.19
    83.9 2237.23     105 2237.95   121.8 2233.18   168.2 2229.55   180.8 2229.38
   204.8 2225.47   218.5 2224.58   225.6 2222.77     231 2221.35   244.9 2222.32
   252.1 2224.08   265.9 2225.29   302.6 2224.27   311.8 2221.38     322    2223
   332.1 2220.09   350.5 2217.83   362.6 2219.95   367.7 2222.61   376.5 2228.45
   393.1 2242.41   397.2 2244.83   408.3 2248.99   428.6 2249.63     438 2253.59
#Mann= 3 ,-1,0
       0      .1       0   225.6    .045       0   244.9      .1       0
#XS Ineff= 2 , 0
                          269.86         2229.37
Permanent Ineff=
       F       F
Bank Sta=225.6,244.9
XS Rating Curve= 0 ,0
Exp/Cntr(USF)=0,0
Exp/Cntr=0.3,0.1

Type RM Length L Ch R = 1 ,10230   ,142.4,138.5,132.7
XS GIS Cut Line= 4
2220282.34006163666370.0239468222220488.13731228666409.318567497
2220549.41028011666445.9491460912220724.57104685666563.166997594
#Sta/Elev= 30
       0 2261.54    17.9 2254.81      35 2251.24    50.7 2246.48    75.2 2237.81
    87.4 2232.71   132.2 2227.35   188.9 2226.85   218.2 2222.88   230.52219.443
   238.6 2217.78   250.3 2219.24   264.9 2222.72   285.2 2222.79   316.9 2221.43
   322.7 2220.72   331.4 2218.27     342 2217.17   351.6 2217.92   358.6 2220.11
   366.1 2224.87   380.2 2235.93   390.1 2241.37   400.6  2243.2   409.4  2246.6
   428.6 2247.37   440.9  2253.1   462.3 2259.29   475.5 2260.45   491.7 2264.88
#Mann= 3 ,-1,0
       0      .1       0   230.5    .045       0   250.3      .1       0
#XS Ineff= 2 , 0
                          280.56         2226.81
Permanent Ineff=
       F       F
Bank Sta=230.5,250.3
XS Rating Curve= 0 ,0
Exp/Cntr(USF)=0,0
Exp/Cntr=0.3,0.1

Type RM Length L Ch R = 1 ,10091   ,179.7,180.1,180.1
XS GIS Cut Line= 3
2220252.88446449 666503.951934012220554.21670171 666573.58035275
2220724.75437485666618.244981428
#Sta/Elev= 30
       0 2253.29    11.6 2250.01    81.4  2225.1    93.7 2223.71   118.3 2215.83
   126.5 2215.88     143 2218.95   159.4 2219.54   175.8 2218.44   196.3 2218.52
   200.4 2217.91   208.6 2213.72     221 2212.35   230.5 2213.45   241.5 2216.01
   260.5 2217.55   274.3 2217.23   290.8 2214.66     299 2214.44   307.1 2217.18
   327.8 2227.12   340.2 2231.05     363  2235.6   377.5  2241.8   386.6 2243.72
   410.5 2244.47   418.8 2248.76     434 2253.06   448.2 2258.24   485.6 2265.57
#Mann= 3 ,-1,0
       0      .1       0   208.6    .045       0   230.5      .1       0
#XS Ineff= 2 , 0
                          265.63         2221.08
Permanent Ineff=
       F       F
Bank Sta=208.6,230.5
XS Rating Curve= 0 ,0
Exp/Cntr(USF)=0,0
Exp/Cntr=0.3,0.1

Type RM Length L Ch R = 1 ,9911    ,120.8,125.4,131
XS GIS Cut Line= 4
2220189.97880112666688.0098761422220393.57804483666719.560277902
2220501.38221677 666746.054523552220720.84036162 666789.72800842
#Sta/Elev= 30
       0 2251.71    46.7 2236.52    58.9 2234.21      67 2230.49    83.2 2225.75
   103.4 2217.92   115.6 2216.89   135.8 2211.95   164.1 2208.25   184.4 2209.71
   229.3    2210   240.1    2208   249.9 2206.41   258.1 2206.77     262 2208.05
   266.4 2210.05   274.6 2211.24   295.2 2211.42   319.9 2210.21   360.7 2211.69
   368.8    2214   385.1 2222.65   397.4 2226.86   438.2 2235.01   458.6 2239.98
   470.8 2241.07   487.1 2245.36   511.6 2246.69   527.9 2253.36   540.8 2255.75
#Mann= 3 ,-1,0
       0      .1       0   240.1    .045       0     262      .1       0
#XS Ineff= 2 , 0
          196.73 2213.04
Permanent Ineff=
       F       F
Bank Sta=240.1,262
XS Rating Curve= 0 ,0
Exp/Cntr(USF)=0,0
Exp/Cntr=0.3,0.1

Type RM Length L Ch R = 1 ,9786    ,135,130,119.5
XS GIS Cut Line= 4
2220211.35966248666768.3066475182220340.45059041666815.174054474
2220448.16340289666885.0640473042220648.78879407666907.264397967
#Sta/Elev= 30
       0 2235.25    30.7 2227.45    43.4 2222.62    54.4 2221.66    60.6 2219.93
      69 2219.26    81.7 2216.18     103 2212.64   147.3  2206.9   161.7 2206.85
   170.4 2205.47   179.9 2205.69   182.82205.256   189.5 2204.36   202.2 2205.25
   214.5 2206.48   243.9 2205.49   251.4  2205.9   285.9 2205.18     310 2205.63
     314 2206.43   326.1 2212.06   334.2 2215.05   341.9 2216.66   366.4 2218.56
   390.5 2217.29   402.6 2218.32   414.7 2218.22   430.7 2219.78   467.6  2225.5
#Mann= 3 ,-1,0
       0      .1       0   182.8    .045       0   202.2      .1       0
#XS Ineff= 2 , 0
          161.97 2208.74  231.83         2207.89
Permanent Ineff=
       F       F
Bank Sta=182.8,202.2
XS Rating Curve= 0 ,0
Exp/Cntr(USF)=0,0
Exp/Cntr=0.3,0.1

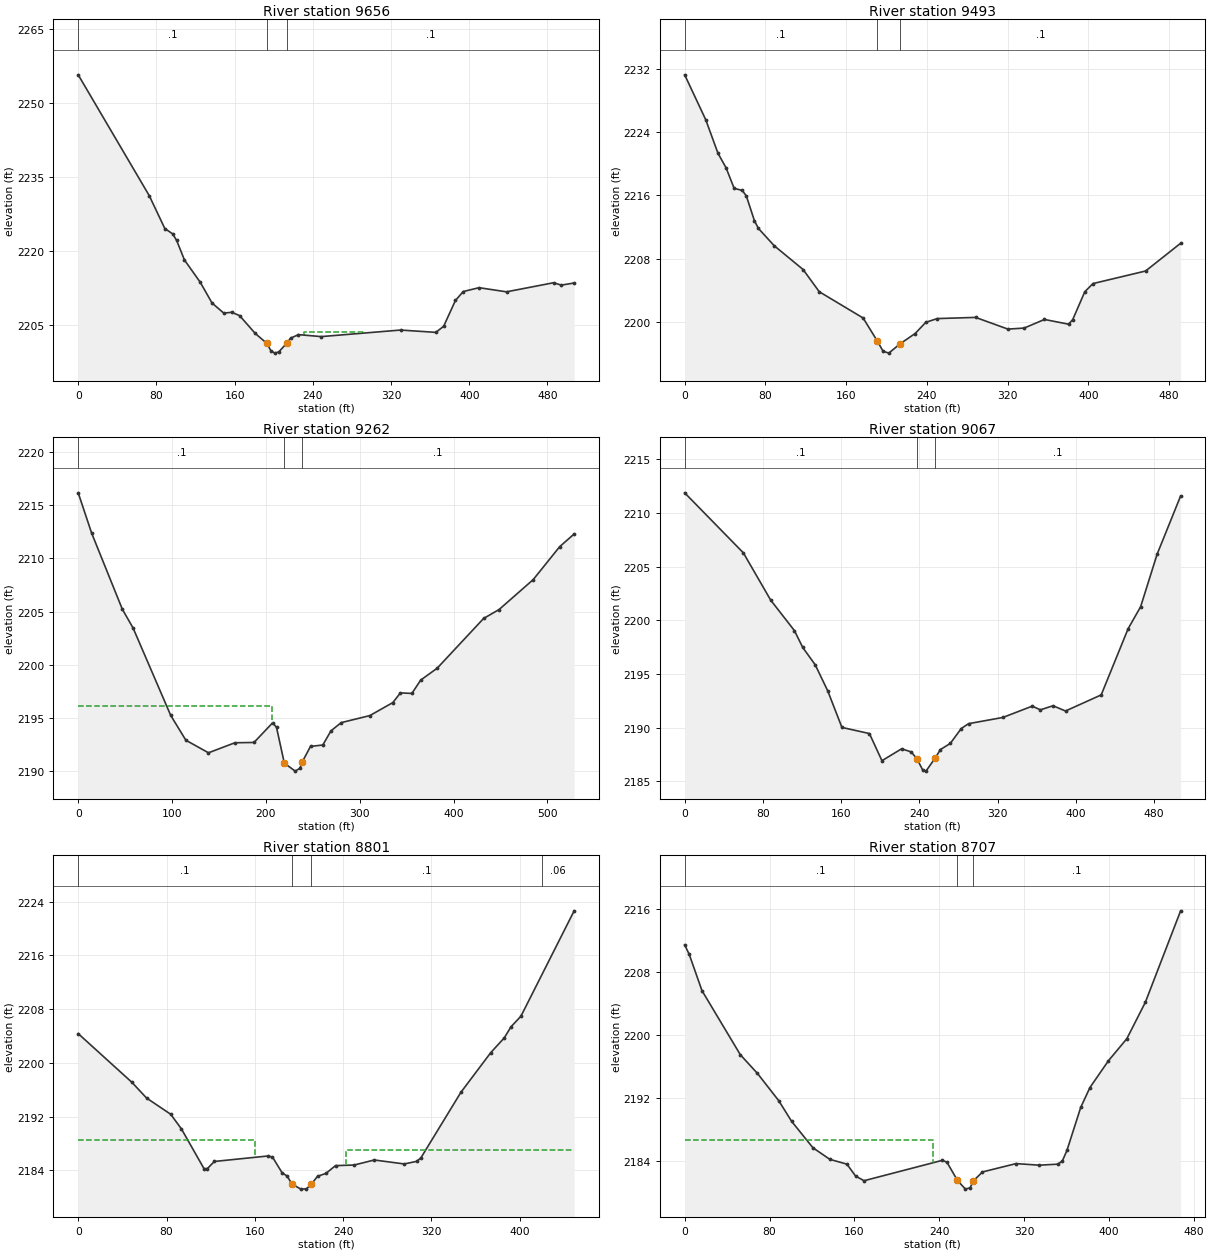
Type RM Length L Ch R = 1 ,9656    ,177.5,162.8,148.9
XS GIS Cut Line= 3
2220123.95459342666928.6165718432220398.94659135666955.110817491
2220629.17245008666974.296305719
#Sta/Elev= 30
       0  2255.7    72.6 2231.22    88.6 2224.53    96.7 2223.44   100.7 2222.11
   108.7 2218.15   124.8 2213.65   136.9 2209.43   148.9 2207.38   156.9 2207.55
     165 2206.89   181.1 2203.26     1932201.238   197.1 2199.75   201.1 2199.27
   205.2 2199.52   213.1 2201.25   217.2  2202.3   225.3 2203.02   248.6 2202.62
   329.7 2203.95   365.8 2203.48   373.8 2204.71   385.9 2209.96   393.9 2211.76
     410 2212.54   438.1  2211.7   486.2 2213.54   494.2 2213.06   507.3 2213.49
#Mann= 3 ,-1,0
       0      .1       0     193    .045       0   213.1      .1       0
#XS Ineff= 1 ,-1
230.5807291.8667 2203.48
Permanent Ineff=
       T
Bank Sta=193,213.1
XS Rating Curve= 0 ,0
Exp/Cntr(USF)=0,0
Exp/Cntr=0.3,0.1

Type RM Length L Ch R = 1 ,9493    ,210.2,231.4,243.2
XS GIS Cut Line= 4
2220163.33187749667128.9289722552220315.77428538667142.249182653
2220386.07539582667069.7280371532220622.84004896667053.821839414
#Sta/Elev= 30
       0 2231.26    20.9 2225.57      33 2221.33      41  2219.5      49  2216.9
    57.1 2216.63    61.1 2215.93    69.1  2212.8    73.1 2211.82    88.6 2209.65
   117.3 2206.63   133.3 2203.82   176.8 2200.49   190.8 2197.59   196.5  2196.3
   202.2 2196.05   213.5 2197.24   228.3 2198.53   238.9 2199.95   250.2 2200.42
   288.2 2200.57   320.2 2199.09   336.3 2199.22   356.4 2200.31   380.3 2199.71
   384.4 2200.29   396.4 2203.82   404.5 2204.85   456.6 2206.44   491.3 2209.95
#Mann= 3 ,-1,0
       0      .1       0   190.8    .045       0   213.5      .1       0
Bank Sta=190.8,213.5
XS Rating Curve= 0 ,0
Exp/Cntr(USF)=0,0
Exp/Cntr=0.3,0.1

Type RM Length L Ch R = 1 ,9262    ,194.3,194.8,197
XS GIS Cut Line= 4
2220197.94887703667252.3359064932220400.81792086 667270.94683853
2220518.30217657667302.1161308612220719.26600672667331.458876327
#Sta/Elev= 30
       0 2216.14    14.3 2212.36      47 2205.22    58.5 2203.45    98.6 2195.25
   114.7 2192.93   138.8 2191.75   166.9 2192.69   187.3 2192.72   207.2 2194.57
   211.3 2194.13   219.6 2190.78   231.2 2190.03   236.2  2190.3   238.82190.909
   247.5 2192.35   260.6 2192.48   269.3 2193.81   280.2 2194.58   310.7 2195.24
   335.2 2196.46   343.3 2197.37   355.5 2197.32   364.9 2198.57   382.5 2199.69
   431.9 2204.35   448.4 2205.19   484.8    2208     513 2211.09   528.4 2212.28
#Mann= 3 ,-1,0
       0      .1       0   219.6    .045       0   238.8      .1       0
#XS Ineff= 2 , 0
          206.87 2196.14
Permanent Ineff=
       F       F
Bank Sta=219.6,238.8
XS Rating Curve= 0 ,0
Exp/Cntr(USF)=0,0
Exp/Cntr=0.3,0.1

Type RM Length L Ch R = 1 ,9067    ,263.3,266.4,264.3
XS GIS Cut Line= 2
2220166.97853156667381.3411069462220642.56372324667557.389731372
#Sta/Elev= 30
       0 2211.88      60 2206.29      88 2201.88   112.2 2199.05   120.7 2197.48
   133.5 2195.86   146.3 2193.43   160.8 2190.03   188.9 2189.46   201.7 2186.93
   221.8 2188.04   231.6 2187.75   237.4 2187.12   243.6 2186.03   246.7 2185.96
   256.1 2187.17   261.5 2187.97   271.6 2188.54   282.8 2189.93   290.3 2190.38
   325.4 2190.96   355.3 2192.01   363.8 2191.67   376.6 2192.05   389.4 2191.56
   425.9 2193.06   453.4 2199.22   466.2 2201.27   483.1 2206.17   507.1 2211.59
#Mann= 3 ,-1,0
       0      .1       0   237.4    .045       0   256.1      .1       0
Bank Sta=237.4,256.1
XS Rating Curve= 0 ,0
Exp/Cntr(USF)=0,0
Exp/Cntr=0.3,0.1

Type RM Length L Ch R = 1 ,8801    ,93.8,93.5,93
XS GIS Cut Line= 2
2220131.82207037 667614.585731652220541.11248589667800.045451185
#Sta/Elev= 30
       0 2204.35    48.7 2197.09    61.9 2194.76    83.8 2192.34    93.5 2190.16
     114 2184.23   117.1 2184.26   123.3 2185.31   171.5 2186.12     176 2185.97
   184.8  2183.6   189.2 2183.15   193.6 2181.96   201.7 2181.19   206.8 2181.23
   211.2 2181.92   216.8  2183.1   224.4 2183.53   233.1 2184.69     250 2184.78
   268.2 2185.53   295.4 2184.94   306.7 2185.33   310.5 2185.86   346.7 2195.61
   373.7 2201.51     386 2203.72   392.1 2205.37   401.1 2206.95   449.3 2222.64
#Mann= 4 ,-1,0
       0      .1       0   193.6    .045       0   211.2      .1       0
     420     .06       0
#XS Ineff= 2 , 0
          160.56 2188.48  242.82         2187.04
Permanent Ineff=
       F       F
Bank Sta=193.6,211.2
XS Rating Curve= 0 ,0
Exp/Cntr(USF)=0,0
Exp/Cntr=0.3,0.1

Type RM Length L Ch R = 1 ,8707    ,155.9,157.9,160.3
XS GIS Cut Line= 3
2220023.90527814667747.3101609622220245.68678127667769.288508119
2220470.79833699667865.194022985
#Sta/Elev= 30
       0  2211.5     4.3 2210.28    16.3 2205.67    52.5  2197.5    68.6 2195.13
    88.7 2191.65   100.8 2189.03   120.9 2185.66   136.9 2184.18     153 2183.57
   161.1 2182.06   169.1 2181.46     243 2184.06   247.3 2183.81   257.22181.497
   264.7 2180.39   269.1 2180.56   272.22181.444   280.8 2182.58   312.5 2183.64
   334.4 2183.44   351.7 2183.57     356 2183.95   360.4 2185.31   373.4 2190.79
   382.1 2193.33   399.5 2196.73   416.9 2199.55   434.3 2204.17   467.6 2215.83
#Mann= 3 ,-1,0
       0      .1       0   257.2    .045       0   272.2      .1       0
#XS Ineff= 2 , 0
          234.08 2186.63
Permanent Ineff=
       F       F
Bank Sta=257.2,272.2
XS Rating Curve= 0 ,0
Exp/Cntr(USF)=0,0
Exp/Cntr=0.3,0.1

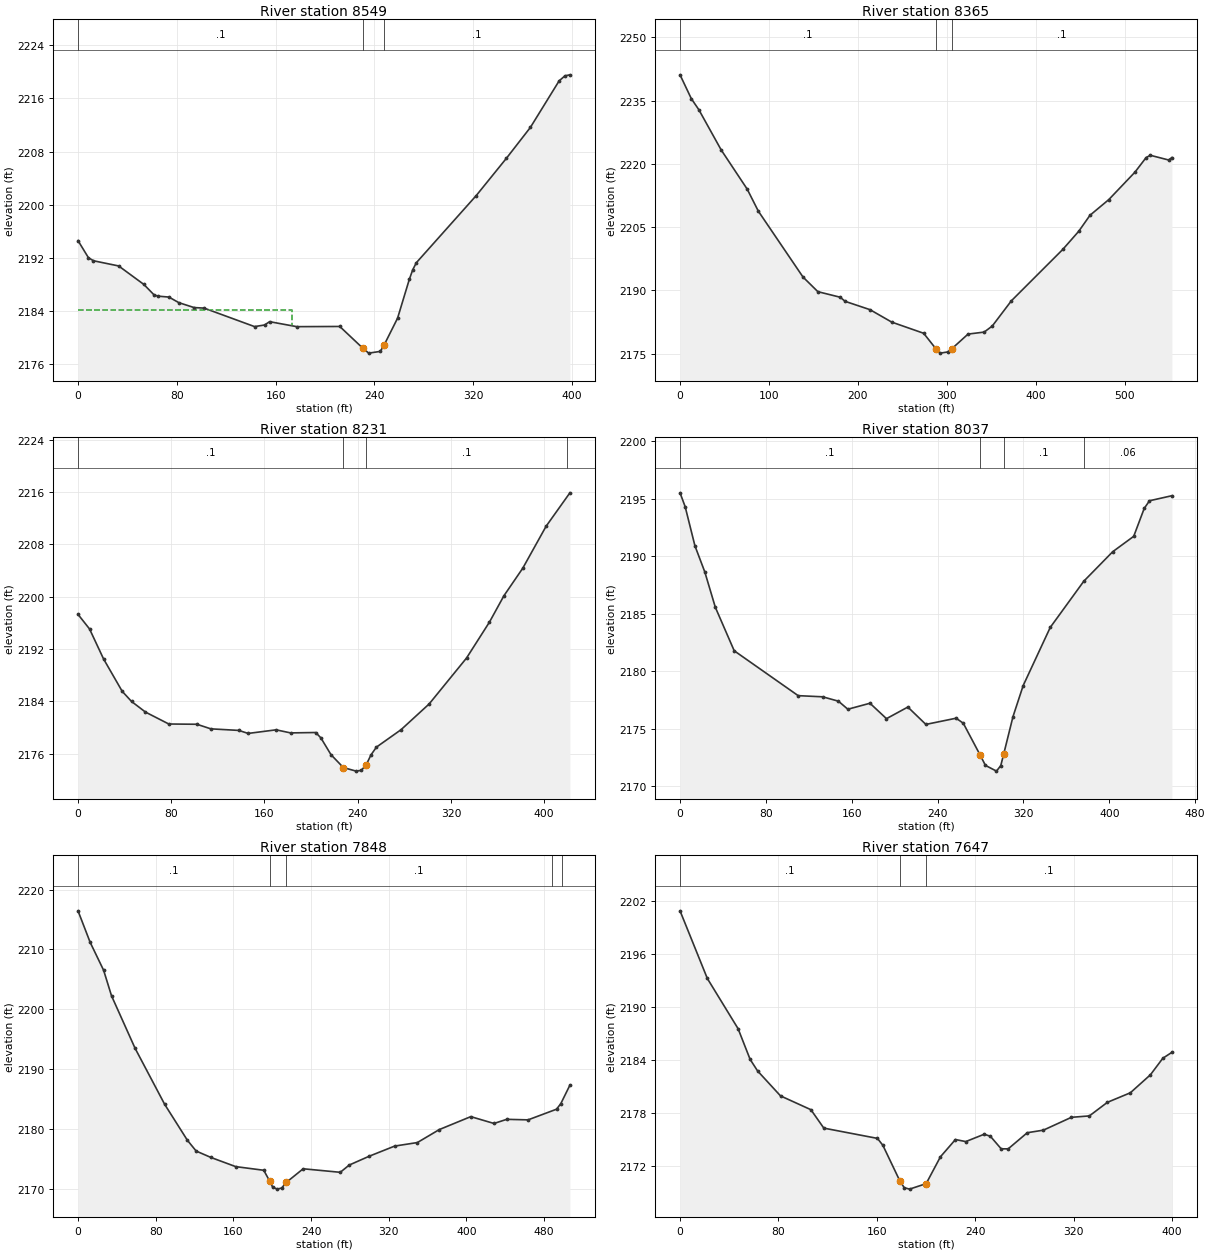
Type RM Length L Ch R = 1 ,8549    ,184.5,184,182.5
XS GIS Cut Line= 3
2220031.89740438667873.8521597442220210.38822371667908.484706779
2220395.53914824668020.374474123
#Sta/Elev= 30
       0 2194.62     8.4 2192.06    12.5 2191.59    32.9 2190.81    53.3 2188.03
    61.4 2186.49    64.5 2186.27    73.6 2186.13    81.6 2185.29      94 2184.55
   102.1 2184.47   142.9 2181.69     151 2181.93   155.1 2182.43   177.1 2181.68
   211.9 2181.71   230.32178.488   235.3  2177.7   244.7 2177.96   247.7 2178.88
   258.7 2182.96   268.2 2188.79     271 2190.25   273.9  2191.3   322.4  2201.4
   346.8    2207   366.2 2211.64   389.5 2218.65   394.2  2219.4   398.2 2219.55
#Mann= 3 ,-1,0
       0      .1       0   230.3    .045       0   247.7      .1       0
#XS Ineff= 2 , 0
          173.07 2184.13
Permanent Ineff=
       F       F
Bank Sta=230.3,247.7
XS Rating Curve= 0 ,0
Exp/Cntr(USF)=0,0
Exp/Cntr=0.3,0.1

Type RM Length L Ch R = 1 ,8365    ,146,134.8,121
XS GIS Cut Line= 4
2219851.98005771667968.3797708152220091.54488426668041.467345016
 2220186.9647728668092.2226048782220371.71391869668152.113811514
#Sta/Elev= 30
       0 2241.12    12.7 2235.46    21.1 2232.86    46.2 2223.32    75.5    2214
      88 2208.78   138.2 2193.15   154.9 2189.68     180 2188.36   185.6 2187.38
   213.5 2185.41   237.9 2182.46   273.8 2179.81   287.4 2176.17   292.4  2175.1
     301 2175.38   305.5 2176.15   323.7 2179.62   341.8 2180.09   350.9 2181.53
   372.4 2187.52   430.1 2199.69   448.1 2204.01   460.7  2207.8   481.8 2211.51
   511.2 2218.02   523.8 2221.49   528.6 2222.03     549 2220.92   552.8  2221.5
#Mann= 3 ,-1,0
       0      .1       0   287.4    .045       0   305.5      .1       0
Bank Sta=287.4,305.5
XS Rating Curve= 0 ,0
Exp/Cntr(USF)=0,0
Exp/Cntr=0.3,0.1

Type RM Length L Ch R = 1 ,8231    ,176,193.3,215.3
XS GIS Cut Line= 4
2219906.33292828668205.2438152762220084.03385913668213.497683649
2220169.00015121668178.0546018112220320.48994205668191.859593866
#Sta/Elev= 30
       0  2197.3     9.9 2195.07    21.9  2190.5    37.9 2185.55    45.9    2184
    57.9 2182.37    77.9 2180.55     102 2180.51     114 2179.81     138 2179.57
     146 2179.11     170 2179.66   182.4 2179.19     204 2179.25   208.4 2178.43
   217.1 2175.86   227.72173.894   238.7 2173.35   243.1 2173.47   247.4 2174.35
   251.4 2175.83   256.1 2177.02   277.2 2179.68   301.3 2183.61   333.4 2190.63
   353.1 2196.13   365.5 2200.15   381.6 2204.34   401.7 2210.77   422.1 2215.87
#Mann= 4 ,-1,0
       0      .1       0   227.7    .045       0   247.4      .1       0
  419.95     .06       0
Bank Sta=227.7,247.4
XS Rating Curve= 0 ,0
Exp/Cntr(USF)=0,0
Exp/Cntr=0.3,0.1

Type RM Length L Ch R = 1 ,8037    ,187.6,189,192.9
XS GIS Cut Line= 4
2219912.00348985668212.5799211522220122.16680946 668329.50176798
2220173.22761599668398.3228550372220281.26932255668474.544058981
#Sta/Elev= 30
       0 2195.51     4.8  2194.3    13.9  2190.9    23.1 2188.63    32.9 2185.56
    50.5 2181.78   110.1 2177.88   132.9 2177.78   147.6  2177.4   156.4  2176.7
     177 2177.22   192.4 2175.88   212.3 2176.89   229.1 2175.38   257.3 2175.92
     264 2175.48   279.72172.714   284.6 2171.82   294.9 2171.32   298.9  2171.8
   301.7 2172.83   310.3 2176.06   319.8 2178.76     345 2183.81   376.3 2187.83
   403.2 2190.39   422.8 2191.73   432.6 2194.16   437.5 2194.82   458.4 2195.26
#Mann= 4 ,-1,0
       0      .1       0   279.7    .045       0   301.7      .1       0
  376.19     .06       0
Bank Sta=279.7,301.7
XS Rating Curve= 0 ,0
Exp/Cntr(USF)=0,0
Exp/Cntr=0.3,0.1

Type RM Length L Ch R = 1 ,7848    ,208,201.2,190.6
XS GIS Cut Line= 3
2219838.01213365668281.2178381162219905.35319733 668290.83799007
2220127.02644148668669.265810621
#Sta/Elev= 30
       0 2216.44    12.5 2211.18    26.4  2206.5    34.5 2202.25    58.8 2193.47
    89.3  2184.1   112.7  2178.1   121.7 2176.31   136.9 2175.24   162.4 2173.71
   191.3  2173.1   197.5 2171.26   200.5 2170.27   205.2 2169.95   209.8 2170.14
   214.4 2171.06   231.9 2173.35   270.1 2172.76   279.3 2173.97   299.8 2175.44
   326.1 2177.14   349.5 2177.73   372.1  2179.9   404.5 2182.06   428.4 2180.92
   441.6 2181.61   463.5 2181.52   492.8  2183.3   497.2 2184.22   506.6 2187.32
#Mann= 5 ,-1,0
       0      .1       0   197.5    .045       0   214.4      .1       0
  488.02     .06       0  498.02      .1       0
Bank Sta=197.5,214.4
XS Rating Curve= 0 ,0
Exp/Cntr(USF)=0,0
Exp/Cntr=0.3,0.1

Type RM Length L Ch R = 1 ,7647    ,143.6,152.9,160.1
XS GIS Cut Line= 4
2219753.97169844 668452.171828452219882.73373229668545.413301237
2219943.41469077668571.3137103442220048.49635058668711.175919524
#Sta/Elev= 30
       0 2200.87    22.2 2193.23    47.2 2187.56      57 2184.09    63.1 2182.78
    81.7 2179.97   106.4 2178.41   116.9 2176.33   160.5 2175.17   164.9 2174.39
   178.8 2170.34   182.3  2169.6   186.6 2169.44   200.1 2170.06   211.7 2173.09
   223.9 2175.04   232.3 2174.81   247.3 2175.64   252.3 2175.41   261.1 2173.99
   266.8 2173.99   282.3 2175.81   295.4  2176.1   318.2 2177.55   332.8 2177.71
   347.4 2179.24   366.1 2180.32   382.4 2182.35   392.5 2184.22   399.9 2184.89
#Mann= 3 ,-1,0
       0      .1       0   178.8    .045       0   200.1      .1       0
Bank Sta=178.8,200.1
XS Rating Curve= 0 ,0
Exp/Cntr(USF)=0,0
Exp/Cntr=0.3,0.1