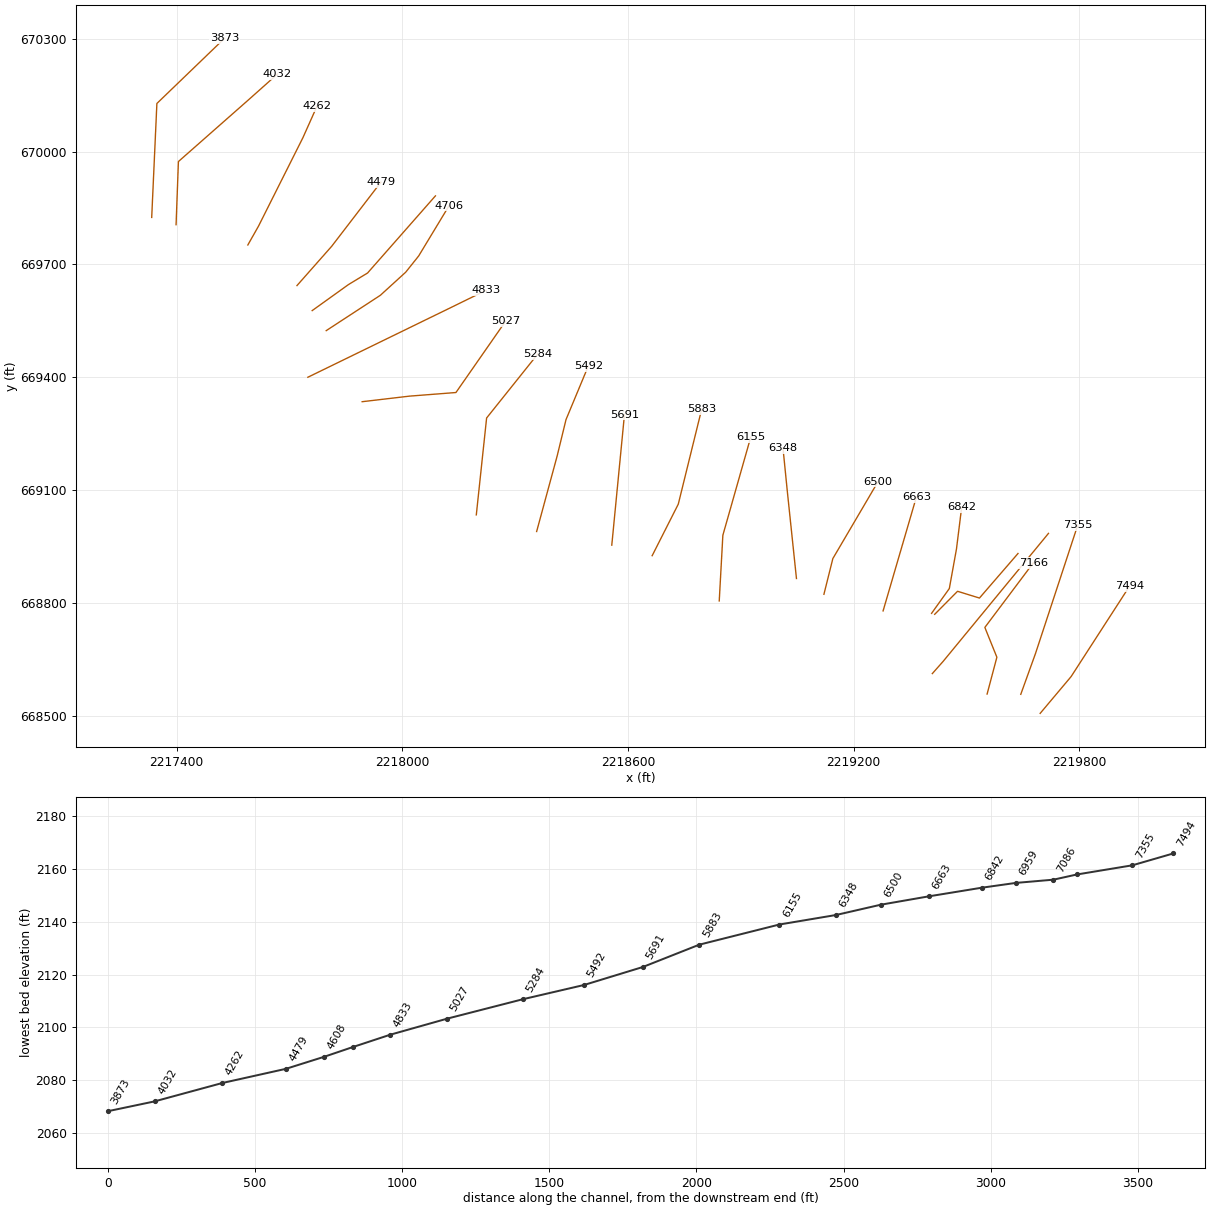
HEC-RAS study JACKSONFK.prj: JACKSONFK

--- JACKSONFK.g01 (geometry) --- (continued)

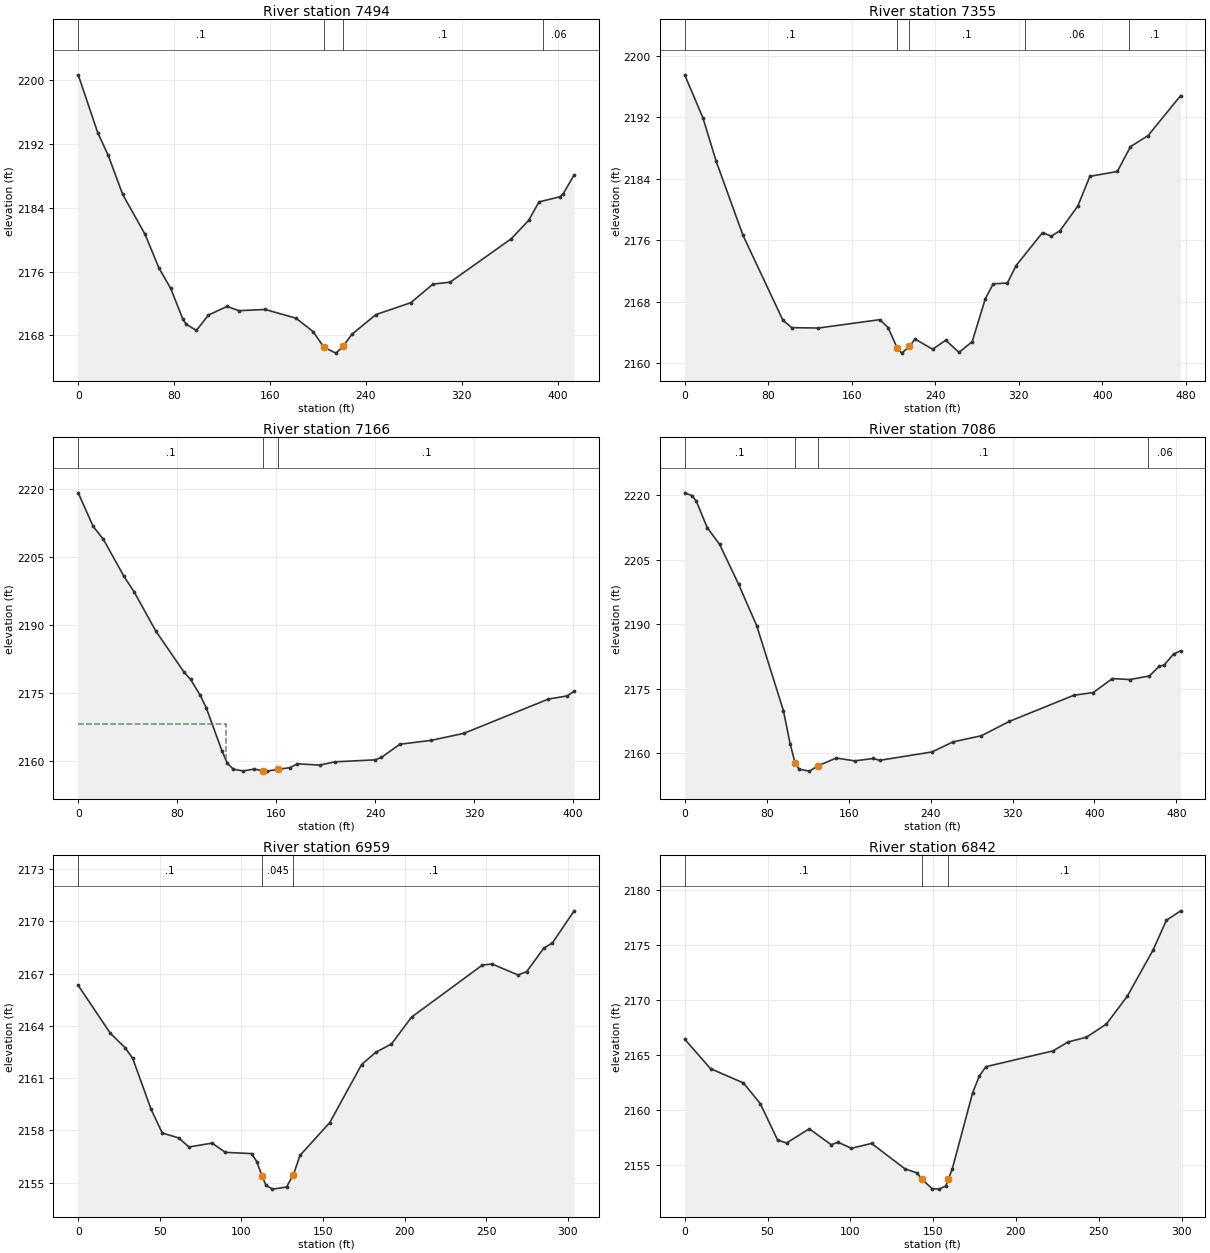
Type RM Length L Ch R = 1 ,7494    ,136.8,139.7,142.1
XS GIS Cut Line= 3
 2219696.2873305668506.0739144232219778.51085148668603.828544917
2219933.82194665668844.103945102
#Sta/Elev= 30
       0 2200.65    16.3  2193.4      25 2190.57    37.1 2185.67    55.8 2180.66
    67.4 2176.43    77.2 2173.88    87.3 2170.04    90.1  2169.4    98.6 2168.62
   108.6 2170.55   124.2 2171.63   134.1  2171.1     156 2171.25   181.7 2170.16
     196 2168.48   205.1  2166.5   215.1 2165.78     221 2166.63   228.3 2168.13
   248.4 2170.61   277.5  2172.1     296 2174.43   310.3 2174.67   361.4 2180.12
   375.8 2182.41   384.5 2184.73   401.9 2185.37   404.7 2185.75   413.8 2188.12
#Mann= 4 ,-1,0
       0      .1       0   205.1    .045       0     221      .1       0
  387.74     .06       0
Bank Sta=205.1,221
XS Rating Curve= 0 ,0
Exp/Cntr(USF)=0,0
Exp/Cntr=0.3,0.1

Type RM Length L Ch R = 1 ,7355    ,179.9,188.6,195.3
XS GIS Cut Line= 3
2219644.73457392668556.7244179352219683.95519343668665.506136186
2219796.23375056669006.780669822
#Sta/Elev= 30
       0 2197.53    17.5 2191.92    30.2 2186.25    55.8 2176.64      94 2165.58
   102.5  2164.6   127.9 2164.55   186.9 2165.64   194.8  2164.6   203.32162.009
   207.9 2161.28   215.2 2162.15   220.6 2163.12   237.4 2161.79     250 2162.96
   262.7 2161.38   275.3 2162.77   287.9 2168.37   295.5 2170.31     309 2170.41
   317.4 2172.69   342.7 2176.98   351.1 2176.51   359.5 2177.25   376.4 2180.43
     388 2184.31   414.3 2184.94   426.9 2188.18   443.7 2189.61   474.9 2194.82
#Mann= 5 ,-1,0
       0      .1       0   203.3    .045       0   215.2      .1       0
  325.64     .06       0  425.64      .1       0
Bank Sta=203.3,215.2
XS Rating Curve= 0 ,0
Exp/Cntr(USF)=0,0
Exp/Cntr=0.3,0.1

Type RM Length L Ch R = 1 ,7166    ,96,79.6,65.1
XS GIS Cut Line= 4
2219555.21108887668557.4574762032219581.18549914668655.361022629
2219549.21699419668734.6162744982219677.75702453668905.780978114
#Sta/Elev= 30
       0 2219.22    12.1 2211.81    20.4 2208.93      37 2200.78    45.2 2197.37
    62.7 2188.73    85.6 2179.62    90.8 2178.05    98.7  2174.5   103.5 2171.77
   116.2 2162.27   120.5 2159.56   125.4 2158.23   133.4 2157.85   142.1 2158.27
   149.42157.892   152.6 2157.81   161.82158.235   171.1 2158.57   177.2 2159.44
     195 2159.14   207.8 2159.87     240  2160.3     245 2160.84     260 2163.75
     285 2164.59   311.6 2166.14     380 2173.71   395.1  2174.4   400.8 2175.43
#Mann= 3 ,-1,0
       0      .1       0   149.4    .045       0   161.8      .1       0
#XS Ineff= 2 , 0
          119.15 2168.12
Permanent Ineff=
       F       F
Bank Sta=149.4,161.8
XS Rating Curve= 0 ,0
Exp/Cntr(USF)=0,0
Exp/Cntr=0.3,0.1

Type RM Length L Ch R = 1 ,7086    ,147.1,127.4,110
XS GIS Cut Line= 3
2219409.58586102668611.8832142932219437.90729603668643.859028006
2219718.38086202668984.629842717
#Sta/Elev= 30
       0 2220.61     7.1 2219.95    11.3 2218.71      22  2212.5    34.1 2208.62
    52.6 2199.35    70.3  2189.7    96.4 2169.92   102.9 2162.26   107.8 2157.71
   111.8 2156.29   121.8 2155.85   130.5 2157.14     148  2158.9   165.9 2158.24
   184.3  2158.8   190.2 2158.36   241.3 2160.31     262 2162.66   289.7 2164.09
   316.9 2167.42   379.9 2173.51   398.8 2174.14   417.5 2177.39   434.6 2177.16
   453.7    2178     463 2180.22     468 2180.53   477.2  2183.1   484.1 2183.84
#Mann= 4 ,-1,0
       0      .1       0   107.8    .045       0   130.5      .1       0
  452.71     .06       0
Bank Sta=107.8,130.5
XS Rating Curve= 0 ,0
Exp/Cntr(USF)=0,0
Exp/Cntr=0.3,0.1

Type RM Length L Ch R = 1 ,6959    ,93.8,116.8,139.8
XS GIS Cut Line= 4
2219415.92052227668769.502908657 2219476.6107309668830.678638953
2219534.87333118668812.7143371992219637.31840334668931.181624438
#Sta/Elev= 30
       0 2166.32    19.7 2163.57    28.8 2162.74    33.4 2162.13    44.6 2159.22
    51.5 2157.85    61.5 2157.57    67.8 2157.05      82 2157.27    90.2 2156.74
   106.2 2156.67   109.4 2156.21   112.6 2155.39     115 2154.85     119 2154.63
   127.6 2154.75   131.8 2155.46   135.9 2156.57   154.1 2158.45   173.6 2161.78
   182.4 2162.49   191.9 2162.96   204.2  2164.5   247.6 2167.49   253.5 2167.55
   269.4 2166.92   274.7 2167.11   285.2 2168.46   290.5 2168.76   303.8  2170.6
#Mann= 3 ,-1,0
       0      .1       0   112.6    .045       0   131.8      .1       0
Bank Sta=112.6,131.8
XS Rating Curve= 0 ,0
Exp/Cntr(USF)=0,0
Exp/Cntr=0.3,0.1

Type RM Length L Ch R = 1 ,6842    ,182.9,179.2,175.4
XS GIS Cut Line= 4
2219407.51836791668772.0153511982219454.76225579668837.961463988
2219473.69760088668942.8341444952219487.53984801669053.730779101
#Sta/Elev= 30
       0 2166.42    15.6 2163.74    35.5 2162.44    45.7 2160.55    56.1 2157.26
    61.5 2156.99    75.2 2158.28    88.5 2156.83    92.5 2157.06   100.7 2156.51
   112.8 2156.95   133.2 2154.62   140.2 2154.28   143.22153.697   149.4 2152.84
   153.5  2152.8   157.6 2153.08   159.22153.701   161.6 2154.66   173.8 2161.53
   177.9 2163.08   181.9 2163.92   222.3 2165.35   231.4 2166.16   242.5 2166.59
   254.6 2167.79   267.3 2170.34   282.8 2174.52   290.8 2177.21   299.4 2178.07
#Mann= 3 ,-1,0
       0      .1       0   143.2    .045       0   159.2      .1       0
Bank Sta=143.2,159.2
XS Rating Curve= 0 ,0
Exp/Cntr(USF)=0,0
Exp/Cntr=0.3,0.1

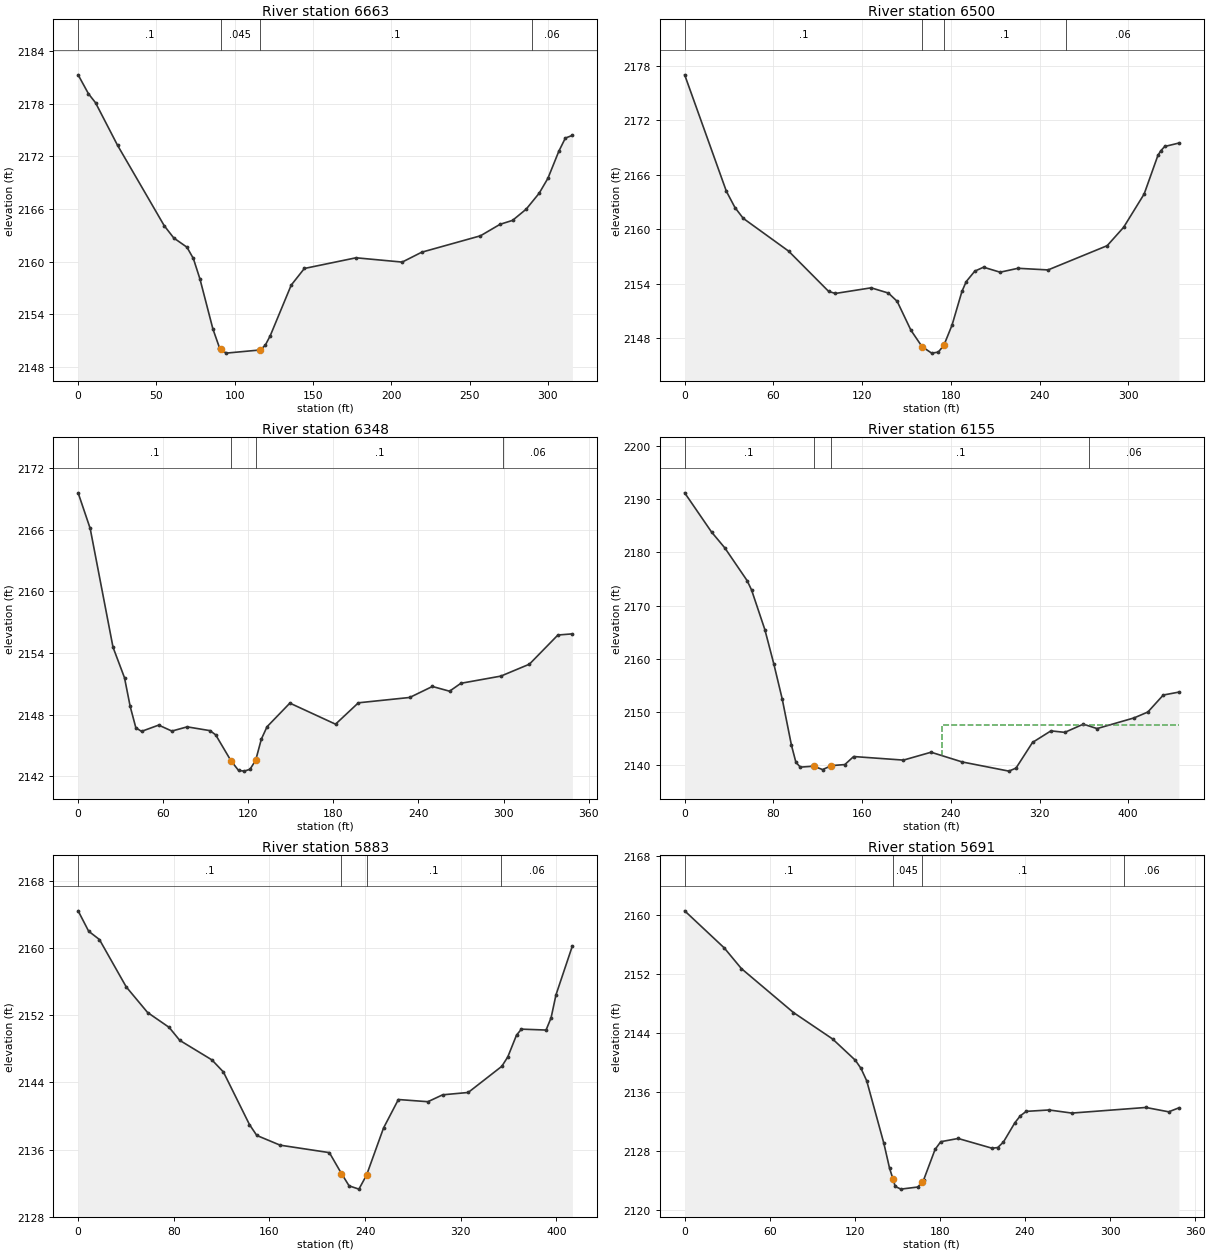
Type RM Length L Ch R = 1 ,6663    ,169.2,163.4,158.8
XS GIS Cut Line= 2
2219278.64833116 668778.516068412219367.22773031669081.550854967
#Sta/Elev= 30
       0 2181.31     6.6 2179.15    11.1 2178.13    25.2 2173.26      55 2164.09
    61.1 2162.69    69.5 2161.64    73.6 2160.35    77.8 2158.02    86.1  2152.3
    90.3 2150.16      91 2150.05    94.5 2149.55   116.2 2149.91   119.5 2150.44
   122.7 2151.53   136.1 2157.31   144.5 2159.21   177.5 2160.43     207 2159.94
   219.5 2161.07     257 2162.94   269.5 2164.25   277.5  2164.7   286.2 2165.98
   294.5  2167.8   300.1 2169.51     307 2172.57   311.2 2174.09   315.7  2174.4
#Mann= 4 ,-1,0
       0      .1       0      91    .045       0   116.2      .1       0
     290     .06       0
Bank Sta=91,116.2
XS Rating Curve= 0 ,0
Exp/Cntr(USF)=0,0
Exp/Cntr=0.3,0.1

Type RM Length L Ch R = 1 ,6500    ,143.8,151.8,159.2
XS GIS Cut Line= 3
2219121.34034736668822.7259074022219145.09380897668917.739753863
2219264.77471173669121.471366948
#Sta/Elev= 30
       0 2177.02    28.2  2164.2      34 2162.41    39.6 2161.22    70.3 2157.61
    97.4 2153.17   101.9 2152.95   126.1 2153.57   137.8 2152.99   143.7 2152.08
     153  2148.9   160.52147.097     167 2146.38   171.5 2146.49   175.32147.254
   180.8 2149.47   187.5 2153.18   190.4 2154.26   196.2 2155.41   202.1 2155.84
   213.3 2155.29   225.4 2155.72   245.7 2155.54   285.7 2158.21   296.8 2160.23
   310.7  2163.9     320 2168.15   321.9 2168.65   324.6 2169.13   334.2 2169.51
#Mann= 4 ,-1,0
       0      .1       0   160.5    .045       0   175.3      .1       0
  257.94     .06       0
Bank Sta=160.5,175.3
XS Rating Curve= 0 ,0
Exp/Cntr(USF)=0,0
Exp/Cntr=0.3,0.1

Type RM Length L Ch R = 1 ,6348    ,195.6,192.6,191.7
XS GIS Cut Line= 3
2219048.31449155668864.6909856212219024.33811284669093.065992897
2219012.49121289669211.318767974
#Sta/Elev= 30
       0 2169.59     8.5 2166.12    24.6 2154.56    32.7 2151.59    36.7  2148.8
    40.7 2146.72    44.7 2146.37    56.8 2146.98    66.1  2146.4    76.9 2146.81
      93 2146.44      97 2146.03   107.82143.504   113.1 2142.57   117.1  2142.5
   121.2 2142.68   125.2 2143.56   129.2 2145.62   133.2 2146.82   149.3 2149.12
   181.5 2147.07   197.6 2149.15   233.8 2149.67   249.8 2150.74   261.9 2150.28
   269.9 2151.05   298.1 2151.75   318.2 2152.91   338.3 2155.75   348.5 2155.86
#Mann= 4 ,-1,0
       0      .1       0   107.8    .045       0   125.2      .1       0
  299.63     .06       0
Bank Sta=107.8,125.2
XS Rating Curve= 0 ,0
Exp/Cntr(USF)=0,0
Exp/Cntr=0.3,0.1

Type RM Length L Ch R = 1 ,6155    ,267.6,272.1,270.4
XS GIS Cut Line= 3
2218842.99772666668805.0121165592218852.61787862668979.654875112
2218926.61904749669240.138989564
#Sta/Elev= 30
       0 2191.16    24.2 2183.81    36.2 2180.82    56.3 2174.68    60.3 2172.93
    72.3 2165.48    80.3 2159.11      88 2152.42    96.3 2143.76   100.3 2140.56
   104.3 2139.65   116.3 2139.83   124.4 2139.19   132.4 2139.94   144.4 2140.13
   152.4 2141.64   197.3 2140.97   222.2 2142.45   250.3 2140.62   292.4  2138.9
   298.8 2139.47   313.7 2144.29   330.3 2146.46   342.8 2146.18   359.5 2147.72
   371.9 2146.89   405.2 2148.89   417.7    2150   431.6 2153.19   445.7 2153.74
#Mann= 4 ,-1,0
       0      .1       0   116.3    .045       0   132.4      .1       0
  364.91     .06       0
#XS Ineff= 2 , 0
                          231.83         2147.59
Permanent Ineff=
       F       F
Bank Sta=116.3,132.4
XS Rating Curve= 0 ,0
Exp/Cntr(USF)=0,0
Exp/Cntr=0.3,0.1

Type RM Length L Ch R = 1 ,5883    ,186.9,191.8,190.8
XS GIS Cut Line= 3
2218664.66899581668925.3223720032218734.10219131 669062.36157363
2218796.22662938669314.513704623
#Sta/Elev= 30
       0 2164.45     8.8 2162.02    17.8 2161.03    40.2 2155.39    58.1 2152.33
    76.1 2150.56      85 2149.01   111.9 2146.68   121.5 2145.24   143.3 2138.97
   149.4 2137.68   168.9 2136.52   210.1 2135.63   220.2 2133.14   226.6 2131.67
   234.8 2131.28   241.22132.955   255.4 2138.57   267.8 2141.96   292.5  2141.7
   304.8 2142.52   326.2  2142.8   354.3 2145.92   359.3 2147.04   366.6 2149.64
   370.7 2150.35   391.3 2150.24   395.5  2151.7   399.6 2154.44   413.3 2160.26
#Mann= 4 ,-1,0
       0      .1       0   220.2    .045       0   241.2      .1       0
  353.63     .06       0
Bank Sta=220.2,241.2
XS Rating Curve= 0 ,0
Exp/Cntr(USF)=0,0
Exp/Cntr=0.3,0.1

Type RM Length L Ch R = 1 ,5691    ,201.5,199.8,193.7
XS GIS Cut Line= 2
2218557.28918371668953.3830713162218591.00082731669300.366329835
#Sta/Elev= 30
       0 2160.53    27.9 2155.51      40 2152.71    76.7 2146.76   104.3 2143.18
   120.4 2140.29   124.4 2139.18   128.4 2137.51   140.5 2129.04   144.5 2125.68
  146.92 2124.22   148.5 2123.21   152.5 2122.84   164.6 2123.13   167.3 2123.83
   168.6 2124.11   176.6 2128.21   180.6 2129.26   192.9  2129.7   216.8 2128.38
   220.8 2128.47   224.8 2129.21   232.9 2131.83   236.7 2132.76   240.9 2133.37
     257 2133.56   273.1 2133.14   325.3  2133.9   341.4 2133.31   348.6 2133.85
#Mann= 4 ,-1,0
       0      .1       0  146.92    .045       0   167.3      .1       0
     310     .06       0
Bank Sta=146.92,167.3
XS Rating Curve= 0 ,0
Exp/Cntr(USF)=0,0
Exp/Cntr=0.3,0.1

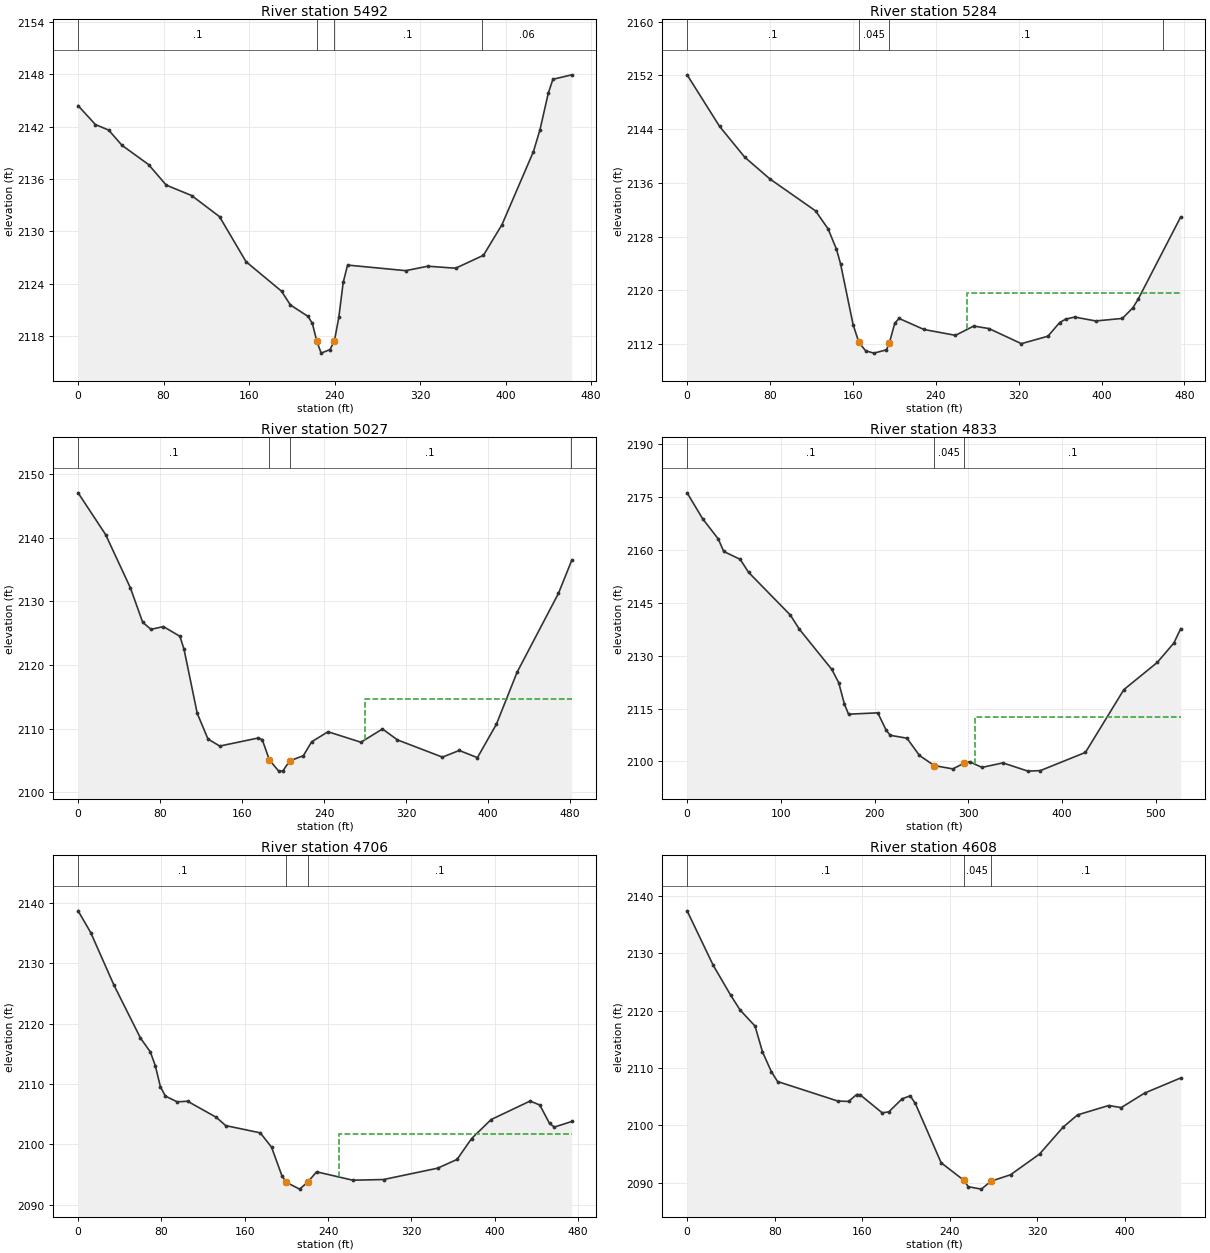
Type RM Length L Ch R = 1 ,5492    ,206,207.8,208.5
XS GIS Cut Line= 4
2218357.48602773668989.5614205462218411.75355158669189.364576518
2218435.59837266669287.2105664792218494.79930776669429.457257768
#Sta/Elev= 30
       0  2144.4    16.2 2142.23    28.6  2141.6    41.1 2139.85    65.9 2137.65
    82.5 2135.29   106.2  2134.1   132.3 2131.68   157.1 2126.52   190.3 2123.14
   198.6 2121.56   215.1 2120.25   219.2 2119.44   223.3  2117.4   227.4 2116.04
   235.7 2116.45   239.8 2117.45   243.9 2120.13     248 2124.14   252.1 2126.13
   306.5 2125.49   327.2    2126   353.2 2125.77   379.2 2127.25   396.5 2130.75
     426 2139.14   432.1 2141.64   439.9 2145.84   444.2 2147.42   461.8 2147.93
#Mann= 4 ,-1,0
       0      .1       0   223.3    .045       0   239.8      .1       0
  377.75     .06       0
Bank Sta=223.3,239.8
XS Rating Curve= 0 ,0
Exp/Cntr(USF)=0,0
Exp/Cntr=0.3,0.1

Type RM Length L Ch R = 1 ,5284    ,284.9,257.1,238.1
XS GIS Cut Line= 3
2218197.08372883669033.8666142592218224.46416132669291.390681956
 2218360.2536461669461.157400932
#Sta/Elev= 30
       0  2152.1    31.3 2144.43    55.6 2139.84    79.8 2136.61     124 2131.84
   136.1 2129.15   144.1 2126.15   148.1 2123.96   160.2  2114.9   165.8 2112.25
   172.3 2111.01   180.3 2110.66   192.4 2111.15   195.32112.239   200.4  2115.1
   204.5 2115.83   228.6 2114.18     259 2113.31   276.6 2114.69   291.3 2114.32
   322.6 2112.07   348.2 2113.18   359.6 2115.22   365.3 2115.72     374 2116.03
   394.4 2115.45   420.1 2115.83   430.3 2117.43   435.4 2118.72   476.4 2130.95
#Mann= 4 ,-1,0
       0      .1       0   165.8    .045       0   195.3      .1       0
  458.98     .06       0
#XS Ineff= 2 , 0
                          270.42         2119.55
Permanent Ineff=
       F       F
Bank Sta=165.8,195.3
XS Rating Curve= 0 ,0
Exp/Cntr(USF)=0,0
Exp/Cntr=0.3,0.1

Type RM Length L Ch R = 1 ,5027    ,187.3,193.5,198
XS GIS Cut Line= 4
2217893.56234972 669334.758570142218019.36433681669349.558803916
2218142.94628884 669359.178955872218274.86225454669548.680824301
#Sta/Elev= 30
       0 2147.06    26.8 2140.51      51 2132.13      63 2126.72    71.1  2125.6
    83.2 2126.04    99.3 2124.51   103.3 2122.49   116.2 2112.41   126.7 2108.36
   138.2 2107.26   175.8 2108.53   179.6 2108.28   186.6 2105.08   195.7 2103.32
   199.7 2103.34   206.3 2104.91   219.8 2105.76   227.8 2107.93   243.8 2109.51
   275.9 2107.86   296.9 2109.95   311.5 2108.23   355.4 2105.52   371.8 2106.57
   389.5 2105.44   408.1 2110.72   428.2 2118.86   468.5 2131.24   481.5 2136.45
#Mann= 4 ,-1,0
       0      .1       0   186.6    .045       0   206.3      .1       0
  480.63     .06       0
#XS Ineff= 2 , 0
                          279.72         2114.64
Permanent Ineff=
       F       F
Bank Sta=186.6,206.3
XS Rating Curve= 0 ,0
Exp/Cntr(USF)=0,0
Exp/Cntr=0.3,0.1

Type RM Length L Ch R = 1 ,4833    ,122.7,127,131.8
XS GIS Cut Line= 3
2217749.24461855669399.7830370492218131.32303774669585.966933185
2218222.68250549669630.733072384
#Sta/Elev= 30
       0 2176.17    16.6 2168.81    33.2 2163.11    39.1 2159.54    56.7  2157.3
    65.6 2153.62   110.1 2141.53   119.9 2137.46   154.5 2126.07   161.8 2122.33
   167.9 2116.25   172.3  2113.4   203.5 2113.78   212.4 2108.87   216.8 2107.41
   234.6 2106.59     248 2101.69   263.7 2098.83   283.6 2097.88   295.4 2099.49
   301.4 2099.92   314.7 2098.31     337 2099.59   363.7 2097.25     377  2097.4
   425.1 2102.56   466.1 2120.36   501.7 2128.06   519.5 2133.59   526.8 2137.67
#Mann= 3 ,-1,0
       0      .1       0   263.7    .045       0   295.4      .1       0
#XS Ineff= 2 , 0
                          306.93         2112.54
Permanent Ineff=
       F       F
Bank Sta=263.7,295.4
XS Rating Curve= 0 ,0
Exp/Cntr(USF)=0,0
Exp/Cntr=0.3,0.1

Type RM Length L Ch R = 1 ,4706    ,96.4,97.7,101.2
XS GIS Cut Line= 5
2217798.03666257669523.7220221792217941.89493487669617.629505486
2218009.16199738669678.9024733172218043.79454442669722.193157112
2218124.38181733669855.395261093
#Sta/Elev= 30
       0 2138.72    12.1 2135.12    34.4 2126.41    59.9 2117.63    69.4 2115.32
    74.2    2113      79 2109.57    83.8 2108.01    95.1 2107.06   105.1 2107.16
   132.7 2104.49   141.7 2103.12   174.9 2101.92   185.7 2099.55   195.7  2094.8
     2002093.701   212.7 2092.59   220.32093.735     229 2095.46   263.7 2094.07
   293.2 2094.18   345.1 2096.06   363.8 2097.51   377.8 2100.98   396.5 2104.12
   433.9 2107.19   443.3 2106.53   452.6 2103.47   457.3 2102.88   473.9  2103.8
#Mann= 3 ,-1,0
       0      .1       0     200    .045       0   220.3      .1       0
#XS Ineff= 2 , 0
                           250.7         2101.75
Permanent Ineff=
       F       F
Bank Sta=200,220.3
XS Rating Curve= 0 ,0
Exp/Cntr(USF)=0,0
Exp/Cntr=0.3,0.1

Type RM Length L Ch R = 1 ,4608    ,130.1,129.9,130.2
XS GIS Cut Line= 5
2217760.74007346669577.0028637722217857.31159884669646.267957842
2217907.92839836669676.9044417582217961.87525047669738.177409589
2218088.41724925669882.035681889
#Sta/Elev= 30
       0 2137.37    23.9 2127.87    39.9 2122.65    48.5 2120.08    62.1  2117.3
    68.9 2112.81    77.1 2109.32    82.7 2107.64   137.6 2104.25   147.6 2104.17
   154.9 2105.37     158 2105.36   178.3 2102.19   184.4 2102.36   196.5 2104.63
   203.9 2105.15   208.6 2103.82   232.2 2093.49   252.7 2090.48   257.1 2089.32
     269  2088.9   277.6 2090.27   295.6  2091.4   322.2 2095.02   343.6 2099.68
   356.9 2101.83   385.3 2103.46   396.8  2103.1   418.1 2105.62   451.2 2108.27
#Mann= 3 ,-1,0
       0      .1       0   252.7    .045       0   277.6      .1       0
Bank Sta=252.7,277.6
XS Rating Curve= 0 ,0
Exp/Cntr(USF)=0,0
Exp/Cntr=0.3,0.1

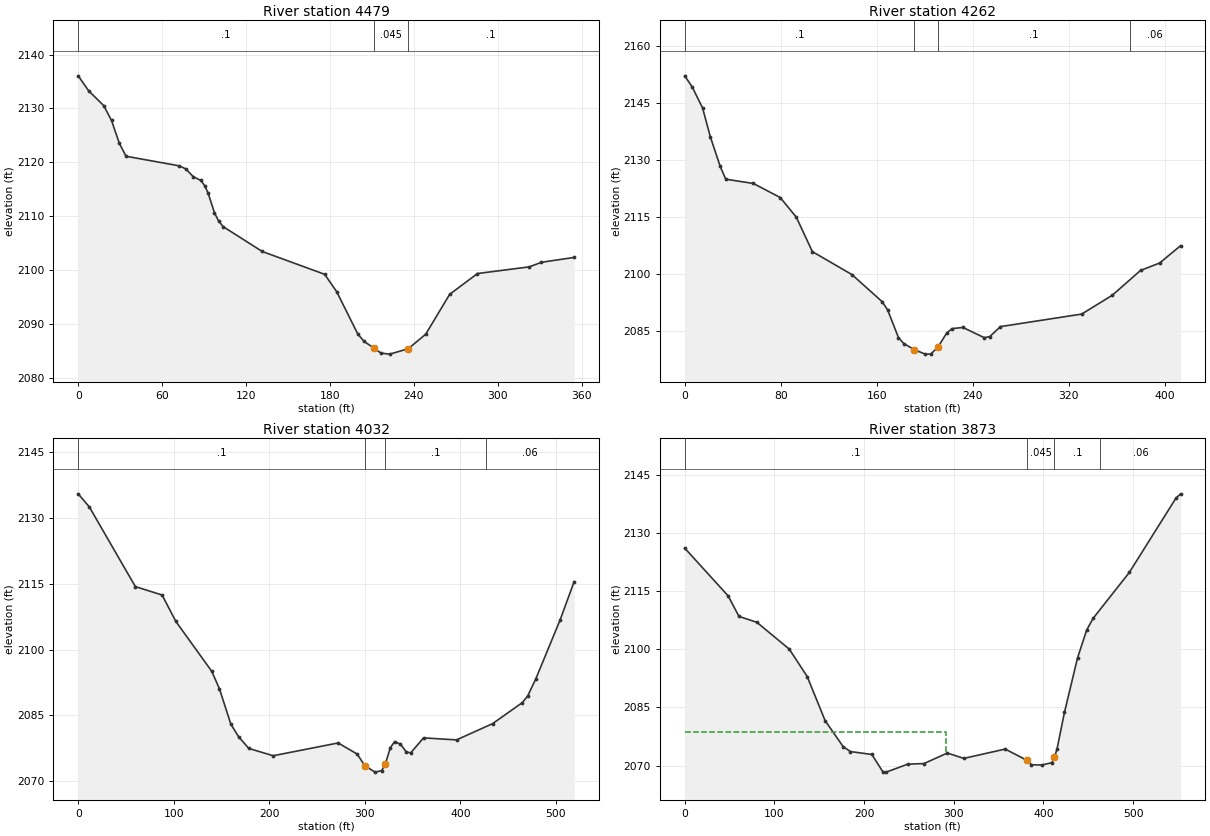
Type RM Length L Ch R = 1 ,4479    ,213,216.5,218.9
XS GIS Cut Line= 3
2217720.27493498669643.5321478252217812.64950793 669748.08798314
2217943.59807837669918.625656276
#Sta/Elev= 30
       0 2136.04     7.5 2133.24    18.2 2130.52    23.8 2127.76    29.4  2123.5
    34.2  2121.1    72.3 2119.32    76.9 2118.75    82.3 2117.29    87.6 2116.62
    90.5 2115.61    92.9 2114.21    97.4  2110.6   100.3 2109.11   103.6 2108.03
   131.5 2103.42   176.2 2099.17   184.7 2095.97   199.9 2088.06   204.4  2086.7
   211.3 2085.49   216.5 2084.53   222.7 2084.35   235.92085.346   248.4 2088.05
   265.5 2095.45   285.4 2099.32   322.5 2100.56   331.1 2101.41   354.5 2102.31
#Mann= 3 ,-1,0
       0      .1       0   211.3    .045       0   235.9      .1       0
Bank Sta=211.3,235.9
XS Rating Curve= 0 ,0
Exp/Cntr(USF)=0,0
Exp/Cntr=0.3,0.1

Type RM Length L Ch R = 1 ,4262    ,234.9,229.8,223.5
XS GIS Cut Line= 4
2217589.60457855669751.4503624542217618.23430476669801.990069114
2217736.08801816670036.7839012352217773.82737361670121.149168856
#Sta/Elev= 30
       0 2152.21     6.1 2149.38    14.9 2143.77    21.4 2136.14    29.6 2128.38
    34.2 2125.01    57.2 2123.89    79.6 2120.19      93 2115.02   106.4 2105.95
   139.4  2099.9   164.6 2092.76   169.1  2090.6   178.1 2083.35   182.5 2081.77
   191.4 2080.15   200.4 2078.98   205.1 2079.03   210.9 2080.77   218.3 2084.53
   222.8 2085.69   231.8    2086   249.6 2083.31   254.1 2083.58   263.1 2086.22
   330.8 2089.52   356.3 2094.48   379.8    2101   395.7 2102.95   413.2 2107.52
#Mann= 4 ,-1,0
       0      .1       0   191.4    .045       0   210.9      .1       0
   370.8     .06       0
Bank Sta=191.4,210.9
XS Rating Curve= 0 ,0
Exp/Cntr(USF)=0,0
Exp/Cntr=0.3,0.1

Type RM Length L Ch R = 1 ,4032    ,158,159,160.4
XS GIS Cut Line= 4
2217398.82698513669805.4567221992217405.04140376669973.269646295
2217591.63138515670137.5802269182217668.21682527670205.810891753
#Sta/Elev= 30
       0  2135.5    11.7 2132.49    59.8 2114.35    87.8 2112.42   102.2  2106.4
   139.8 2095.02   147.8 2091.05   159.8 2082.96   167.9  2080.1   178.6 2077.44
   204.1 2075.78   272.1 2078.69     292 2076.16     300  2073.5   310.7 2072.04
   317.5 2072.37   321.3 2073.78   326.7 2077.62   331.2 2078.99   337.3 2078.44
   343.3 2076.66     348 2076.43   361.5 2079.85     396 2079.39   433.7 2083.09
   464.8 2087.88   470.5 2089.42     479 2093.32   504.5  2106.8   519.1 2115.49
#Mann= 4 ,-1,0
       0      .1       0     300    .045       0   321.3      .1       0
  426.55     .06       0
Bank Sta=300,321.3
XS Rating Curve= 0 ,0
Exp/Cntr(USF)=0,0
Exp/Cntr=0.3,0.1

Type RM Length L Ch R = 1 ,3873    ,310.5,335,362.8
XS GIS Cut Line= 3
2217334.01146352669824.7183209062217347.79696281670127.700447279
2217527.59327415670300.888750234
#Sta/Elev= 30
       0 2126.05    48.5 2113.72    60.5 2108.45    80.5 2106.92   116.6 2100.02
   136.6 2092.95   156.6 2081.57   176.6 2074.92   184.7 2073.62   208.7 2072.87
   220.7 2068.48   224.6 2068.32   248.7 2070.37   266.8 2070.53   292.8 2073.24
   311.2 2071.86   357.3 2074.26   381.6 2071.37   386.6 2070.22     398 2070.15
   409.3 2070.75   412.1  2072.1     415 2074.17   423.4 2083.72     438 2097.76
   448.2 2104.94   455.3 2107.93   495.7 2119.77   547.6 2138.89   552.9 2140.03
#Mann= 4 ,-1,0
       0      .1       0   381.6    .045       0   412.1      .1       0
   463.3     .06       0
#XS Ineff= 2 , 0
          291.04 2078.54
Permanent Ineff=
       F       F
Bank Sta=381.6,412.1
XS Rating Curve= 0 ,0
Exp/Cntr(USF)=0,0
Exp/Cntr=0.3,0.1