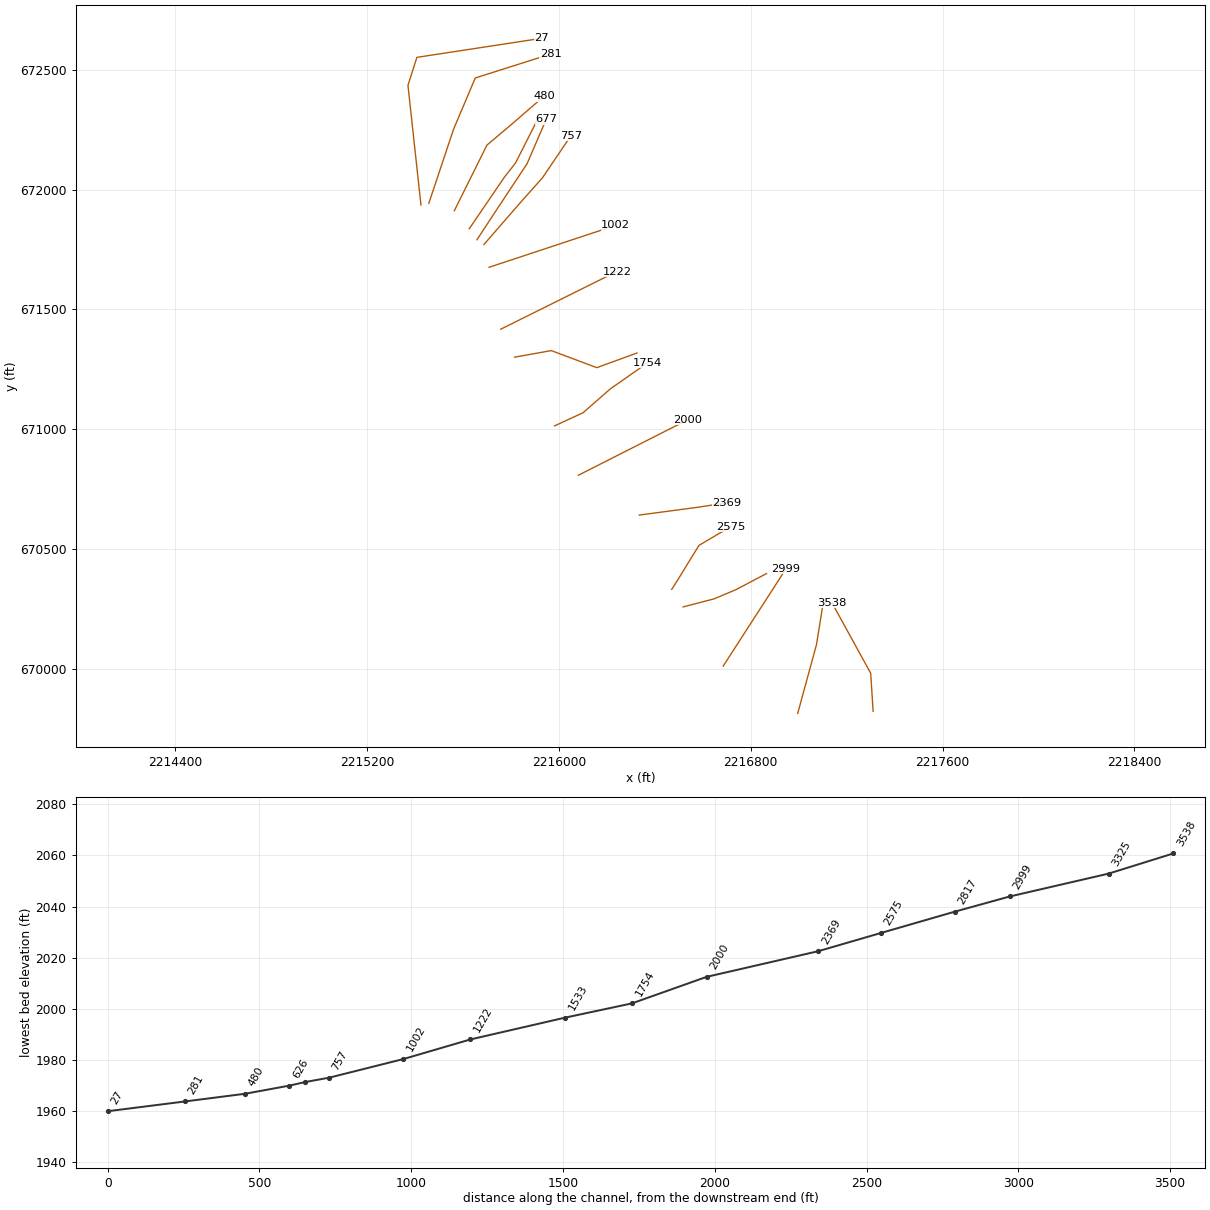
HEC-RAS study JACKSONFK.prj: JACKSONFK

--- JACKSONFK.g01 (geometry) --- (continued)

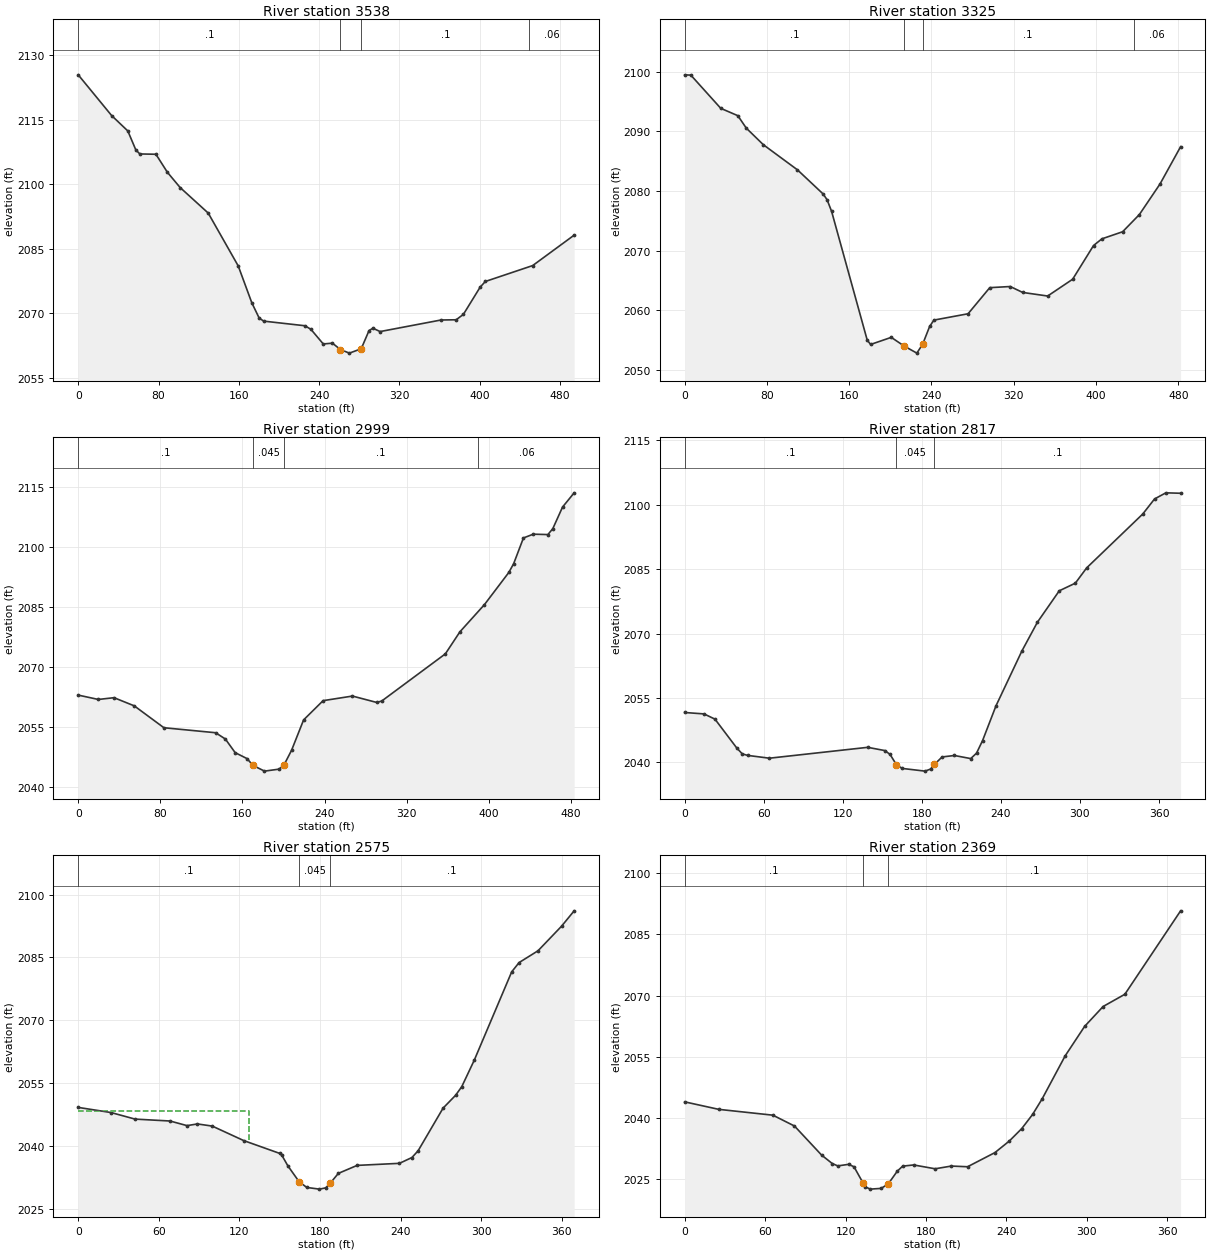
Type RM Length L Ch R = 1 ,3538    ,224.5,213.6,202.7
XS GIS Cut Line= 3
2217310.44464205669823.9021180092217300.29359008669982.935265577
2217139.00465318670276.187878112
#Sta/Elev= 30
       0 2125.45    33.3 2115.98    49.4 2112.41    57.4 2107.99    61.4 2107.06
    77.4 2106.99    88.8 2102.81   101.5 2099.26   129.5 2093.32   159.4 2081.03
   172.9 2072.48   180.2 2068.94   184.7 2068.21   225.9 2067.13   231.8  2066.3
   244.1  2062.9   253.2 2063.09   261.2  2061.6   270.1 2060.77   281.9 2061.78
   289.7 2066.02   293.6 2066.56   300.7 2065.78   361.4 2068.47   376.5 2068.52
   383.7 2069.79   400.3 2076.08   405.5 2077.42   452.7 2081.12     494 2088.19
#Mann= 4 ,-1,0
       0      .1       0   261.2    .045       0   281.9      .1       0
  449.36     .06       0
Bank Sta=261.2,281.9
XS Rating Curve= 0 ,0
Exp/Cntr(USF)=0,0
Exp/Cntr=0.3,0.1

Type RM Length L Ch R = 1 ,3325    ,328.2,325.3,320
XS GIS Cut Line= 3
2216995.96279616669815.3515485652217074.12589634670101.611214186
2217103.61425447670284.859548184
#Sta/Elev= 30
       0 2099.45       6  2099.4    35.1 2093.84    51.7 2092.61    59.9 2090.53
    76.5 2087.75   109.7 2083.54   134.6 2079.51   138.5 2078.54   142.9 2076.58
   177.5 2055.05   180.8 2054.31   200.9  2055.5   213.3 2054.06   225.8 2052.86
   231.52054.379   238.2 2057.32   242.4 2058.39   275.6 2059.45   296.7 2063.82
   316.6 2064.01   328.7 2063.02     353 2062.42   377.3 2065.23   397.6 2070.87
   405.7 2071.99   425.9 2073.18   442.2 2076.06   462.2 2081.16   482.3 2087.42
#Mann= 4 ,-1,0
       0      .1       0   213.3    .045       0   231.5      .1       0
  436.74     .06       0
Bank Sta=213.3,231.5
XS Rating Curve= 0 ,0
Exp/Cntr(USF)=0,0
Exp/Cntr=0.3,0.1

Type RM Length L Ch R = 1 ,2999    ,193.7,182,168.6
XS GIS Cut Line= 2
2216685.21851606670012.7087723862216947.31099814670418.631453115
#Sta/Elev= 30
       0 2062.96    19.6 2061.87    34.9 2062.31    54.6 2060.27    83.5 2054.79
   133.9 2053.54   143.4 2051.96   152.9 2048.56   164.5 2047.06   170.3 2045.36
   181.5 2043.93   195.8 2044.43   200.5 2045.47   207.9 2049.16   219.6 2056.75
   238.6 2061.57   267.2 2062.72     291 2061.11   295.8 2061.49   357.7 2073.28
   371.9  2078.8   395.8 2085.61   419.6 2093.68   424.3 2095.88   433.8  2102.3
   443.4 2103.24   457.6 2103.14   462.4 2104.62   471.9 2110.03   483.2 2113.59
#Mann= 4 ,-1,0
       0      .1       0   170.3    .045       0   200.5      .1       0
     390     .06       0
Bank Sta=170.3,200.5
XS Rating Curve= 0 ,0
Exp/Cntr(USF)=0,0
Exp/Cntr=0.3,0.1

Type RM Length L Ch R = 1 ,2817    ,224.1,242.2,247.9
XS GIS Cut Line= 4
2216517.90772944670259.4216042892216647.82089259670293.133247889
2216739.08900087670331.7783027482216865.71322317670398.379354739
#Sta/Elev= 30
       0 2051.61    14.7 2051.28      23 2050.06    39.5 2043.36    43.7 2041.98
    47.8 2041.62    64.3 2040.97   138.9  2043.5     152 2042.74   155.9 2041.84
   160.7 2039.45   165.1 2038.59   182.4 2037.96   186.7 2038.45   189.5 2039.52
   195.4 2041.26   204.7  2041.6   217.1 2040.88   221.5 2042.14   226.1 2045.08
   236.3 2053.18   255.9 2065.91   267.7 2072.62   284.3 2079.94   296.5 2081.72
   305.1 2085.28   347.7 2097.83   356.6 2101.32   365.2 2102.75   376.4 2102.65
#Mann= 3 ,0,0
       0      .1       0   160.7    .045       0   189.5      .1       0
Bank Sta=160.7,189.5
XS Rating Curve= 0 ,0
Exp/Cntr(USF)=0,0
Exp/Cntr=0.3,0.1

Type RM Length L Ch R = 1 ,2575    ,222.5,206.6,192
XS GIS Cut Line= 4
2216470.44253831670332.5407595412216495.10959461  670371.1858144
2216583.91099726670515.8992113182216716.29086603670594.011556246
#Sta/Elev= 30
       0 2049.18    24.5 2047.95    42.3 2046.39    68.4 2045.93      81 2044.83
    88.8 2045.23    99.8 2044.72   123.3 2041.25   149.9 2038.21   151.4 2037.88
   156.1 2035.23   164.4 2031.47   170.2 2030.06   179.6 2029.66   184.3 2029.96
   187.7 2031.09   193.7 2033.42   207.7 2035.33   239.2 2035.82   248.5 2037.21
   253.1 2038.82   271.7 2049.01     281 2052.07   285.6 2054.13   294.9 2060.45
   322.8 2081.57   328.3 2083.78   342.4  2086.6   359.9 2092.46   369.3 2096.14
#Mann= 3 ,0,0
       0      .1       0   164.4    .045       0   187.7      .1       0
#XS Ineff= 2 , 0
           127.1 2048.34
Permanent Ineff=
       F       F
Bank Sta=164.4,187.7
XS Rating Curve= 0 ,0
Exp/Cntr(USF)=0,0
Exp/Cntr=0.3,0.1

Type RM Length L Ch R = 1 ,2369    ,357.9,368.3,370.6
XS GIS Cut Line= 3
2216334.98953255  670642.47869382216575.26493274670674.454507513
2216701.34099823670693.639995741
#Sta/Elev= 30
       0 2043.94    25.4  2042.1    65.8 2040.67    81.9 2038.01   102.1 2030.89
   110.1  2028.8   114.2 2028.23   122.3 2028.61   126.3 2028.01   133.2 2023.94
   134.4 2023.15   138.4 2022.53   146.5 2022.71   151.8 2023.79   158.6 2026.95
   162.6 2028.17   170.8 2028.46   186.8 2027.52   198.9 2028.19     211 2028.02
   231.4 2031.49   242.1 2034.32   251.4 2037.38   259.5 2040.85   266.7 2044.72
   283.8 2055.23   298.3 2062.45   312.1 2067.33   328.3 2070.33   369.9  2090.8
#Mann= 3 ,-1,0
       0      .1       0   133.2    .045       0   151.8      .1       0
Bank Sta=133.2,151.8
XS Rating Curve= 0 ,0
Exp/Cntr(USF)=0,0
Exp/Cntr=0.3,0.1

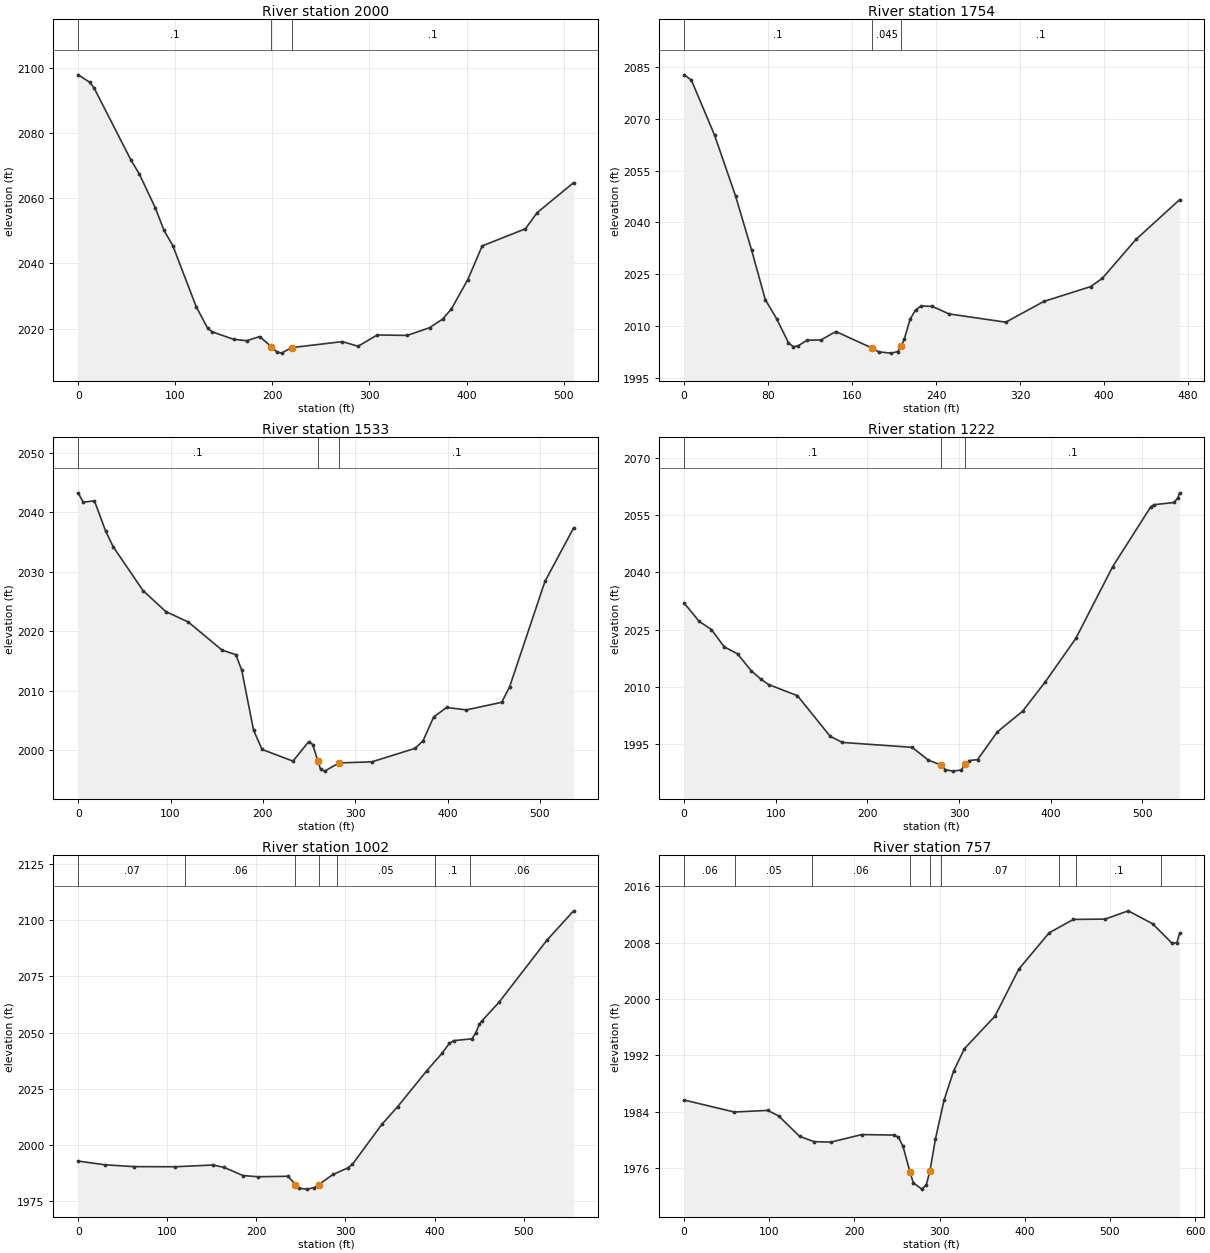
Type RM Length L Ch R = 1 ,2000    ,240.7,246.2,249.6
XS GIS Cut Line= 2
2216081.33758014 670808.702657212216536.47677243671039.379281915
#Sta/Elev= 30
       0 2097.83    12.1 2095.51    16.6 2093.66    54.1 2071.84      63  2067.4
    79.4 2057.05    88.4  2050.1    97.4 2045.48   121.5 2026.74   133.2 2020.19
   137.7 2019.03   160.3 2016.69   173.6 2016.28     187 2017.55   198.9 2014.46
   204.8 2012.79   209.5 2012.47   219.7 2014.16   272.2    2016   288.2 2014.58
   308.1 2018.04   338.8  2017.9   361.9 2020.27   375.4 2022.91   384.4 2026.03
   401.3 2035.03   416.1 2045.36   460.6  2050.6   472.7 2055.55   510.3 2064.77
#Mann= 3 ,-1,0
       0      .1       0   198.9    .045       0   219.7      .1       0
Bank Sta=198.9,219.7
XS Rating Curve= 0 ,0
Exp/Cntr(USF)=0,0
Exp/Cntr=0.3,0.1

Type RM Length L Ch R = 1 ,1754    ,237.9,220.6,201.8
XS GIS Cut Line= 4
2215981.88264458671014.4518402242216100.64995265671069.267520875
2216214.34173475671168.7478302052216370.20684968  671277.7460141
#Sta/Elev= 30
       0 2082.77     6.9 2081.26      29 2065.27      49 2047.65    64.2 2032.05
    77.4 2017.56    88.2 2012.04    99.4 2005.11   103.9 2003.98   108.3 2004.14
   117.1 2005.83   130.4 2005.91   144.6 2008.35   179.3 2003.53   185.3 2002.45
   197.5 2002.09   203.6 2002.55   206.9 2004.11   209.9 2006.29   215.4 2011.97
   220.5 2014.57   225.8 2015.76   236.5 2015.64   252.4 2013.46   306.5 2011.06
   342.7 2017.07   387.3 2021.37   398.4 2023.75   430.5 2035.04   472.1 2046.56
#Mann= 3 ,-1,0
       0      .1       0   179.3    .045       0   206.9      .1       0
Bank Sta=179.3,206.9
XS Rating Curve= 0 ,0
Exp/Cntr(USF)=0,0
Exp/Cntr=0.3,0.1

Type RM Length L Ch R = 1 ,1533    ,296.2,311,323.8
XS GIS Cut Line= 4
2215814.84809777671301.0220249942215968.12898256671328.429865319
2216157.95365444671257.3725015132216325.44601199671318.278813347
#Sta/Elev= 30
       0 2043.23     5.4 2041.66    17.6 2041.89    29.8 2036.78    37.9 2034.18
    70.2 2026.82    94.8  2023.3   119.2 2021.54   155.7 2016.83   170.7 2016.06
   177.1 2013.47   189.9 2003.39   199.2 2000.14   232.6 1998.18   249.7 2001.45
     254 2000.97   259.5 1998.25   262.5  1996.8   266.8  1996.5   282.6 1997.88
   318.1 1998.06     365 2000.33   373.5  2001.6     385  2005.6   399.1 2007.19
   420.4 2006.78   458.7 2008.06   467.2 2010.64   505.5 2028.35   536.6 2037.35
#Mann= 3 ,-1,0
       0      .1       0   259.5    .045       0   282.6      .1       0
Bank Sta=259.5,282.6
XS Rating Curve= 0 ,0
Exp/Cntr(USF)=0,0
Exp/Cntr=0.3,0.1

Type RM Length L Ch R = 1 ,1222    ,223.8,220.8,218.6
XS GIS Cut Line= 2
2215757.51873344671417.703147557 2216241.4791279671658.302850396
#Sta/Elev= 30
       0 2031.99    16.4  2027.2    29.8 2025.06    43.7 2020.53    58.3 2018.69
    73.2 2014.27    83.4 2012.14    92.3 2010.64   123.6 2007.75   159.3 1997.12
   172.7 1995.51   248.7 1994.23   266.5 1990.86   279.9 1989.66     285 1988.38
   293.3    1988   302.3 1988.29   306.7  1989.8   311.2 1990.77   320.1 1991.02
   341.7 1998.28   369.3 2003.69   394.2 2011.44   427.3 2022.73   467.5 2041.52
   508.8 2057.08   512.2 2057.72   534.5 2058.31   538.7  2059.6   540.5 2060.84
#Mann= 3 ,-1,0
       0      .1       0   279.9    .045       0   306.7      .1       0
Bank Sta=279.9,306.7
XS Rating Curve= 0 ,0
Exp/Cntr(USF)=0,0
Exp/Cntr=0.3,0.1

Type RM Length L Ch R = 1 ,1002    ,235.1,244.9,252.5
XS GIS Cut Line= 2
2215708.62837802671675.8857998932216236.59823922671850.553123376
#Sta/Elev= 30
       0 1992.81    29.6 1991.18    62.7 1990.34   109.1 1990.29   151.2 1991.06
   163.8    1990   184.9 1986.38   201.8 1985.84   235.5 1986.06   243.9 1982.29
   248.1 1980.71   256.5 1980.33     265 1980.96   269.8 1982.31     286 1986.84
   302.9 1989.83   307.8 1991.36   340.8 2009.14   358.4 2016.95   391.4  2033.1
   408.2 2040.69   416.6 2045.22   421.7 2046.43   441.9 2047.22   446.1  2049.8
   450.3 2053.66   453.4 2055.33   472.4 2063.52   526.1 2091.13   556.1 2104.18
#Mann= 7 ,-1,0
       0     .07       0     120     .06       0   243.9    .045       0
   269.8     .06       0     290     .05       0     400      .1       0
     440     .06       0
Bank Sta=243.9,269.8
XS Rating Curve= 0 ,0
Exp/Cntr(USF)=0,0
Exp/Cntr=0.3,0.1

Type RM Length L Ch R = 1 ,757     ,77.6,79.4,82.4
XS GIS Cut Line= 4
2215687.24564444671770.9586877432215839.25104169671945.834213739
2215931.15356983672048.8764422652216049.96682101672224.494879214
#Sta/Elev= 30
       0 1985.67    58.9 1983.97    98.3  1984.2   111.2 1983.39   135.5 1980.53
   152.5 1979.77   172.4  1979.7   208.7 1980.77   246.9  1980.7   251.7 1980.39
   257.1 1979.08   265.11975.515   269.1 1973.93   279.1 1973.03   284.4 1973.65
   288.6 1975.59   295.1 1980.14   305.2 1985.65   316.6 1989.83   329.2 1992.96
     365 1997.57     393 2004.24   428.7  2009.4   457.1 2011.29   494.6 2011.34
   521.5 2012.51   550.1 2010.68   572.4 2007.98   578.6 2007.97   581.8 2009.31
#Mann= 9 ,-1,0
       0     .06       0      60     .05       0     150     .06       0
   265.1    .045       0   288.6     .06       0   301.7     .07       0
  439.78     .06       0  459.78      .1       0  559.78     .07       0
Bank Sta=265.1,288.6
XS Rating Curve= 0 ,0
Exp/Cntr(USF)=0,0
Exp/Cntr=0.3,0.1

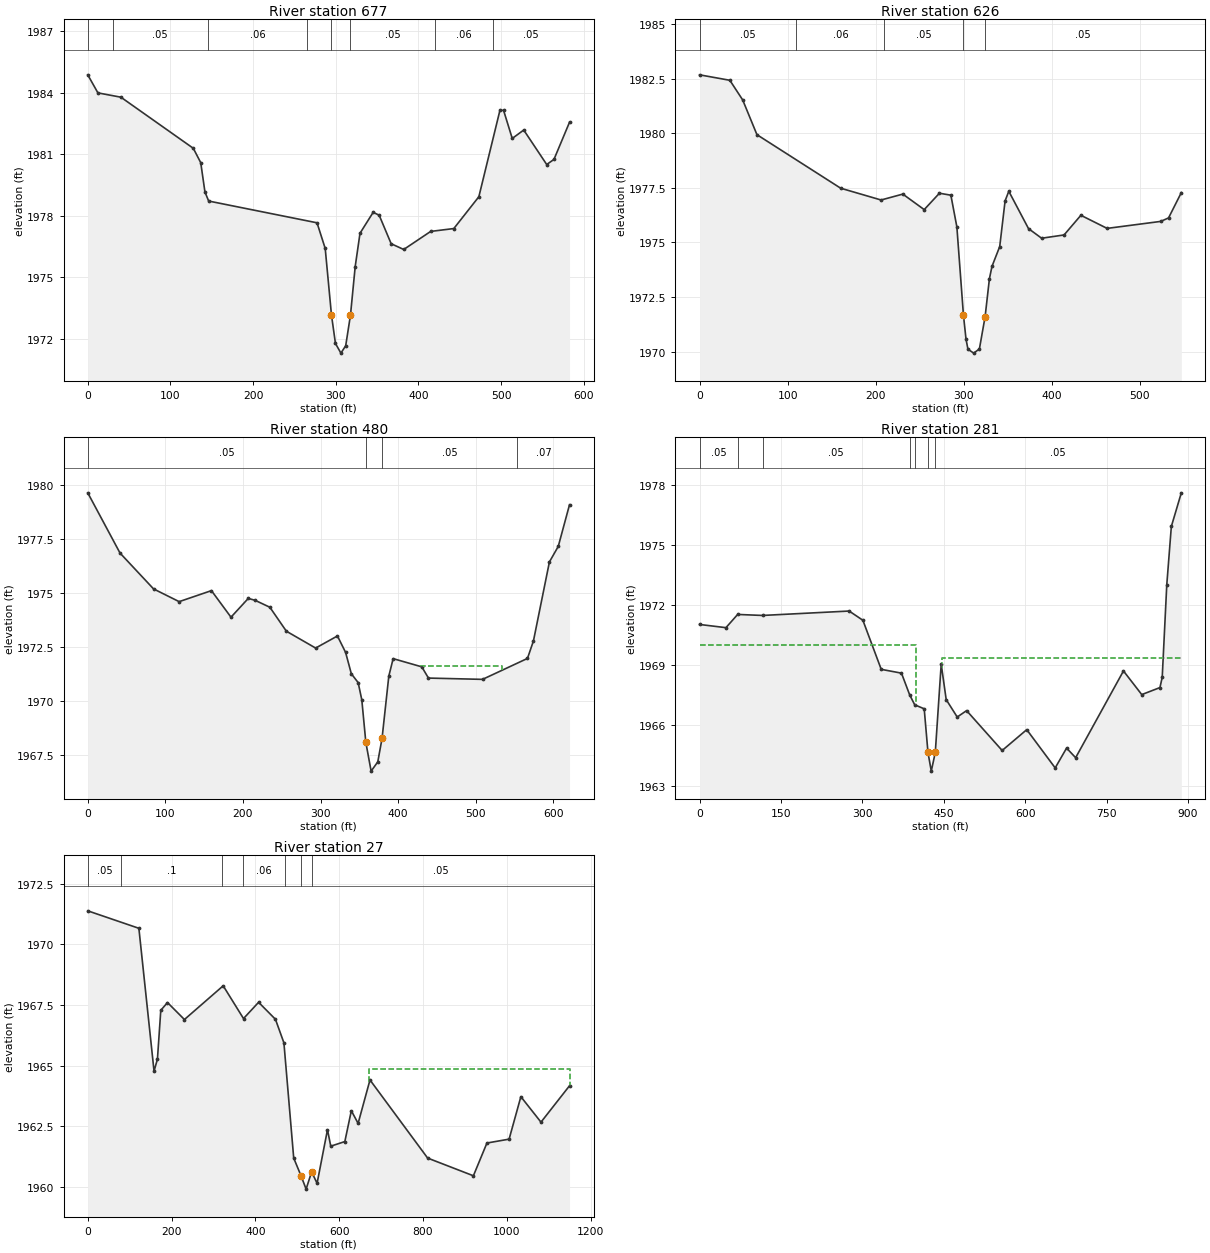
Type RM Length L Ch R = 1 ,677     ,51.8,51.4,50.6
XS GIS Cut Line= 4
2215658.22881315 671790.848651472215726.97832205671895.833398441
2215867.22379591672108.0751237462215947.62012753672294.448437959
#Sta/Elev= 30
       0 1984.87    12.3 1983.99    40.1 1983.78   127.7 1981.29   136.7 1980.59
   141.8 1979.16   146.3 1978.72   277.4 1977.66   287.3 1976.41   294.9 1973.16
   299.7 1971.78   306.3 1971.31   312.1 1971.67   317.9 1973.17   323.6 1975.53
   329.4 1977.15   345.3 1978.17   352.6 1978.03   367.1 1976.64   382.3 1976.36
   414.9 1977.24   442.9 1977.38   473.2 1978.93   498.7 1983.14   503.1 1983.14
   513.6 1981.77   527.5 1982.18   555.3  1980.5   564.1 1980.75   582.9 1982.56
#Mann= 8 ,-1,0
       0     .06       0      30     .05       0  145.49     .06       0
  265.49     .05       0   294.9    .045       0   317.9     .05       0
  419.88     .06       0  489.88     .05       0
Bank Sta=294.9,317.9
XS Rating Curve= 0 ,0
Exp/Cntr(USF)=0,0
Exp/Cntr=0.3,0.1

Type RM Length L Ch R = 1 ,626     ,150,146.2,141.1
XS GIS Cut Line= 5
2215626.03480105671836.7375045242215773.12354413672052.345848418
  2215818.803278672110.8159077792215848.03830768672168.372372462
2215914.73071914672299.930006024
#Sta/Elev= 30
       0 1982.67    34.4 1982.42      49 1981.52    65.2 1979.93   160.3 1977.48
   206.2 1976.94   230.9 1977.21   255.2  1976.5   272.5 1977.25   285.5 1977.16
   292.3 1975.71   299.81971.659   302.7 1970.57   304.9 1970.11   311.4 1969.93
   317.9 1970.12   324.4  1971.6   329.3 1973.34   332.2  1973.9     341 1974.81
   347.1  1976.9   351.3 1977.34   373.7 1975.63   388.6 1975.19   414.1 1975.34
   433.2 1976.24     463 1975.64   523.9 1975.96   532.8 1976.12   547.3 1977.28
#Mann= 5 ,-1,0
       0     .05       0     110     .06       0     210     .05       0
   299.8    .045       0   324.4     .05       0
Bank Sta=299.8,324.4
XS Rating Curve= 0 ,0
Exp/Cntr(USF)=0,0
Exp/Cntr=0.3,0.1

Type RM Length L Ch R = 1 ,480     ,192.4,198.9,204.9
XS GIS Cut Line= 4
2215563.73766343671911.886629607 2215699.7087363672185.473946836
2215797.73447011 672268.045934012215939.28136812672390.541097623
#Sta/Elev= 30
       0 1979.63    41.6 1976.84    84.8 1975.18   117.8 1974.59   159.4  1975.1
   184.6 1973.87   206.9 1974.74   215.8 1974.65   234.7 1974.33     256 1973.22
   293.7 1972.44   321.8    1973   332.3 1972.24   339.7 1971.25   348.5 1970.84
   353.2 1970.04   358.4 1968.07   365.2 1966.74   373.8 1967.17   379.3 1968.26
     388 1971.14   393.6 1971.95   430.5 1971.57   439.1 1971.05   508.8 1970.99
   566.7 1971.96   574.4 1972.77     595 1976.43   606.4 1977.15   620.9 1979.08
#Mann= 4 ,-1,0
       0     .05       0   358.4    .045       0   379.3     .05       0
  553.68     .07       0
#XS Ineff= 1 ,-1
428.2528534.3685 1971.63
Permanent Ineff=
       T
Bank Sta=358.4,379.3
XS Rating Curve= 0 ,0
Exp/Cntr(USF)=0,0
Exp/Cntr=0.3,0.1

Type RM Length L Ch R = 1 ,281     ,251.6,253.6,254.7
XS GIS Cut Line= 4
2215457.47888896671943.0871238382215560.84248949672252.394258819
2215651.07406258 672465.441028612215965.69478826672565.358294717
#Sta/Elev= 30
       0 1971.04    48.6 1970.88    70.2 1971.54   116.1 1971.49   275.6 1971.71
   300.9 1971.25   334.7  1968.8     372 1968.61   387.2 1967.52   396.4 1967.03
   413.9 1966.83   420.8 1964.66   426.9 1963.72   434.3 1964.65   445.2 1969.06
   454.4 1967.29   474.7 1966.42     492 1966.74   557.5 1964.75   602.8 1965.79
   655.2 1963.88   676.2 1964.87   692.9 1964.39     781 1968.72   814.7 1967.54
   848.2 1967.89   852.4  1968.4   860.8 1973.02   869.2 1975.93   887.6 1977.61
#Mann= 7 ,-1,0
       0     .05       0    70.2      .1       0   116.1     .05       0
   387.2      .1       0   396.4     .05       0   420.8    .045       0
   434.3     .05       0
#XS Ineff= 2 , 0
             398    1970   446.2         1969.38
Permanent Ineff=
       F       F
Bank Sta=420.8,434.3
XS Rating Curve= 0 ,0
Exp/Cntr(USF)=0,0
Exp/Cntr=0.3,0.1

Type RM Length L Ch R = 1 ,27      ,,,
XS GIS Cut Line= 4
2215424.53587788671935.8617353942215370.36908478672434.781066218
 2215407.5478348672551.4694277112215926.93636507672630.839792927
#Sta/Elev= 30
       0 1971.38     122 1970.66   158.2 1964.77   166.3 1965.27   174.3 1967.28
   190.3  1967.6   230.7  1966.9   323.2 1968.29   371.7 1966.94   407.7 1967.61
   447.9 1966.91   468.1 1965.94   491.5 1961.19   508.81960.467   521.1 1959.91
   534.2 1960.62   547.3 1960.15   572.1 1962.36   579.9 1961.68   613.5 1961.87
     629 1963.14   645.2 1962.62   673.5 1964.41   811.1 1961.19   920.3 1960.46
   952.6 1961.81  1005.5 1961.97  1033.6 1963.72  1081.6 1962.67  1149.7 1964.17
#Mann= 7 ,-1,0
       0     .05       0      80      .1       0     320     .05       0
     370     .06       0     470     .05       0   508.8    .045       0
   534.2     .05       0
#XS Ineff= 2 , 0
                             672         1964.88
Permanent Ineff=
       F       F
Bank Sta=508.8,534.2
XS Rating Curve= 0 ,0
Exp/Cntr(USF)=0,0
Exp/Cntr=0.3,0.1
LCMann Table=0

Chan Stop Cuts=-1
Use User Specified Reach Order=0
Composite Channel Slope=5